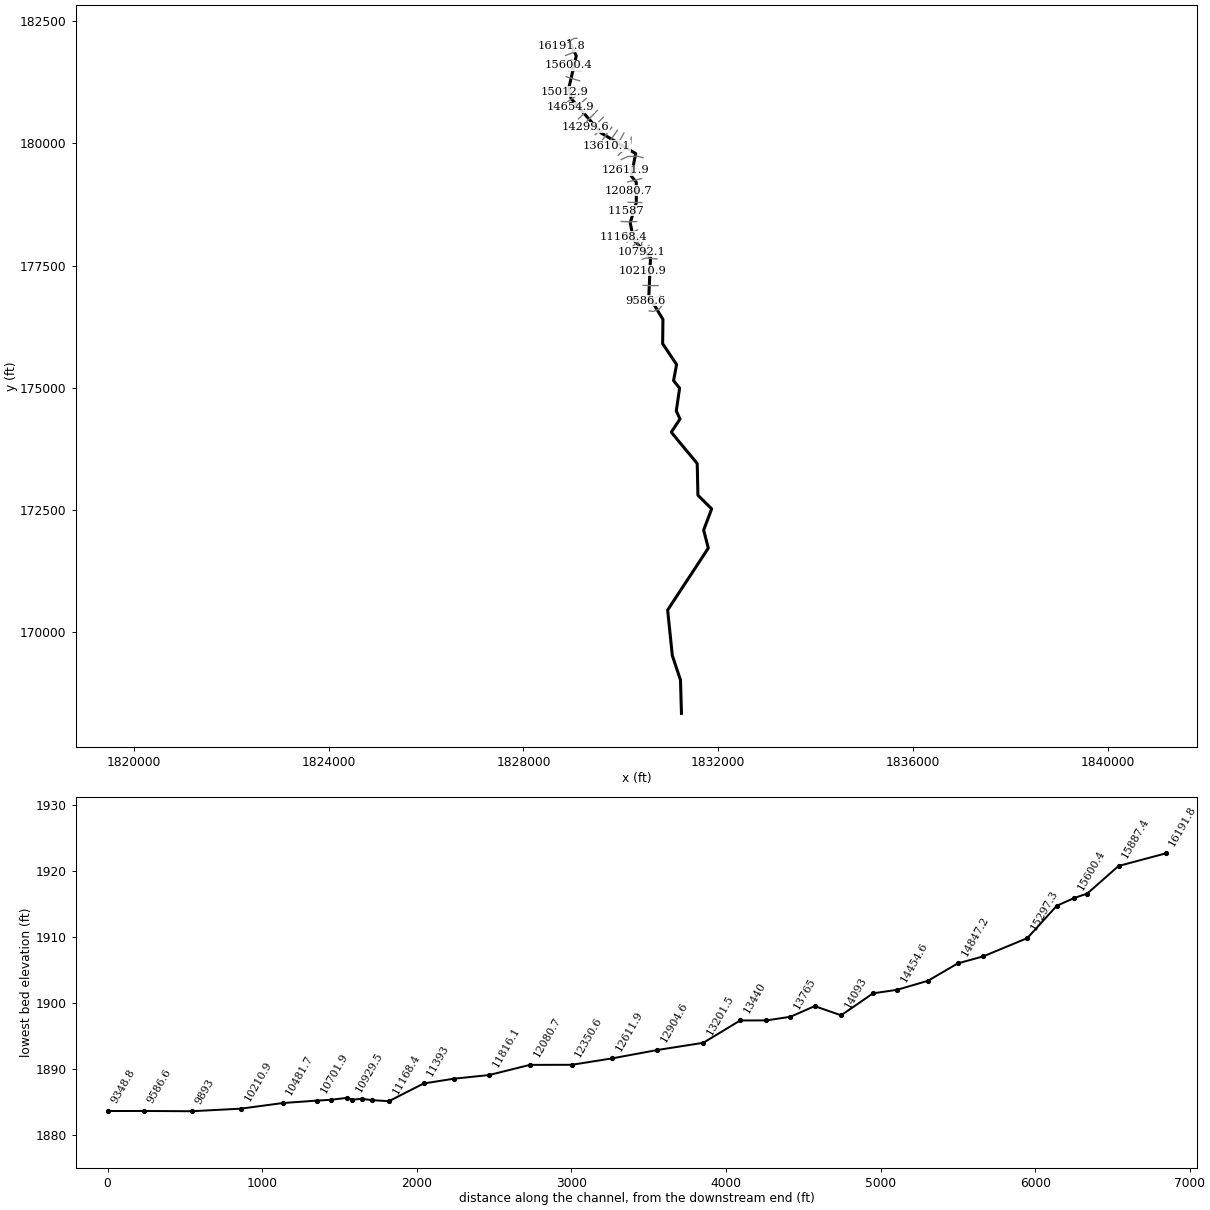
--- ZEBSCK.prj (project) ---

Proj Title=ZEBSCK
Current Plan=p01
Default Exp/Contr=0,0
English Units
Geom File=g01
Flow File=f01
Plan File=p01
BEGIN DESCRIPTION:
END DESCRIPTION:
DSS Export Rating Curves= 0
DSS Export Rating Curve Sorted= 0
DSS Export Volume Flow Curves= 0
DXF OffsetX= 0
DXF OffsetY= 0
DXF ScaleX= 0
DXF ScaleY= 0

--- ZEBSCK.p01 (plan) ---

Plan Title=Floodplain
Program Version=4.00
Geom File=g01
Flow File=f01
K Sum by GR=0
Std Step Tol=0.01
Critical Tol=0.01
Num of Std Step Trials=20
Max Error Tol=0.3
Flow Tol Ratio=0.001
Split Flow NTrial=30
Split Flow Tol=0.02
Split Flow Ratio=0.02
Log Output Level=0
Friction Slope Method=1
Unsteady Friction Slope Method=2
Unsteady Bridges Friction Slope Method=1
Global Log Level=0
CheckData=False
Run HTab=0
Run UNet=0
Run PostProcess=0
UNET Theta=0
UNET Theta Warmup=0
UNET ZTol=0
UNET ZSATol=0
UNET MxIter=0
UNET MaxInSteps=0
UNET DtIC=0
UNET DtMin=0
UNET MaxCRTS=0
UNET WFStab=0
UNET SFStab=0
UNET WFX=0
UNET SFX=0
UNET DSS MLevel=0
UNET DZMax Abort=0
UNET Convert EG Bridges=0
UNET Use Existing IB Tables=0
UNET Froude Limit=0
UNET Froude Power=0
Write IC File=0
Echo Input=False
Echo Output=False
Write Detailed=0

--- ZEBSCK.f01 (steady flow) ---

Flow Title=NFF Regression Equation
Program Version=4.10
Number of Profiles= 1
Profile Names=P100yr
River Rch & RM=ZEBSCK,Main            ,16191.8
553.6898
River Rch & RM=ZEBSCK,Main            ,12904.6
 609.114
River Rch & RM=ZEBSCK,Main            ,12611.9
787.3117
River Rch & RM=ZEBSCK,Main            ,10992
828.7164
River Rch & RM=ZEBSCK,Main            ,8788.6
894.1901
River Rch & RM=ZEBSCK,Main            ,2981.1
971.7225
River Rch & RM=ZEBSCK,Main            ,2530.5
1210.251
River Rch & RM=ZEBSCK,Main            ,475.1
1235.221
River Rch & RM=ZEBSCK,Main            ,268.7
1236.785
Boundary for River Rch & Prof#=ZEBSCK,Main            , 1
Up Type= 0
Dn Type= 3
Dn Slope=0.015
DSS Import GetInterval= 0
DSS Import GetPeak= 0
DSS Import FillOption= 0

--- ZEBSCK.g01 (geometry) ---

Geom Title=USGS 10m DEM
Program Version=4.10

River Reach=ZEBSCK          ,Main
Reach XY= 30
     1828937.937      182093.513     1829084.598      181786.209
     1828932.086      181132.396     1828976.961      180915.471
     1829594.489      180211.221     1830305.021      179790.249
     1830213.785      179331.079     1830317.644      179200.979
     1830317.366      178784.415     1830193.072      178372.751
      1830264.75      178021.625     1830609.998      177662.752
     1830575.125      176873.654     1830864.889      176399.435
     1830858.748      175901.092     1831145.248      175475.655
     1831083.447      175146.798     1831207.132      174991.091
     1831139.002       174524.69     1831215.585      174361.825
     1831036.377      174090.765     1831569.501      173449.125
     1831583.501      172801.953     1831866.375      172522.968
     1831701.251      172088.892     1831796.825      171719.784
     1830961.375      170453.015     1831057.749       169522.92
       1831225.5      169021.547     1831245.581      168339.917

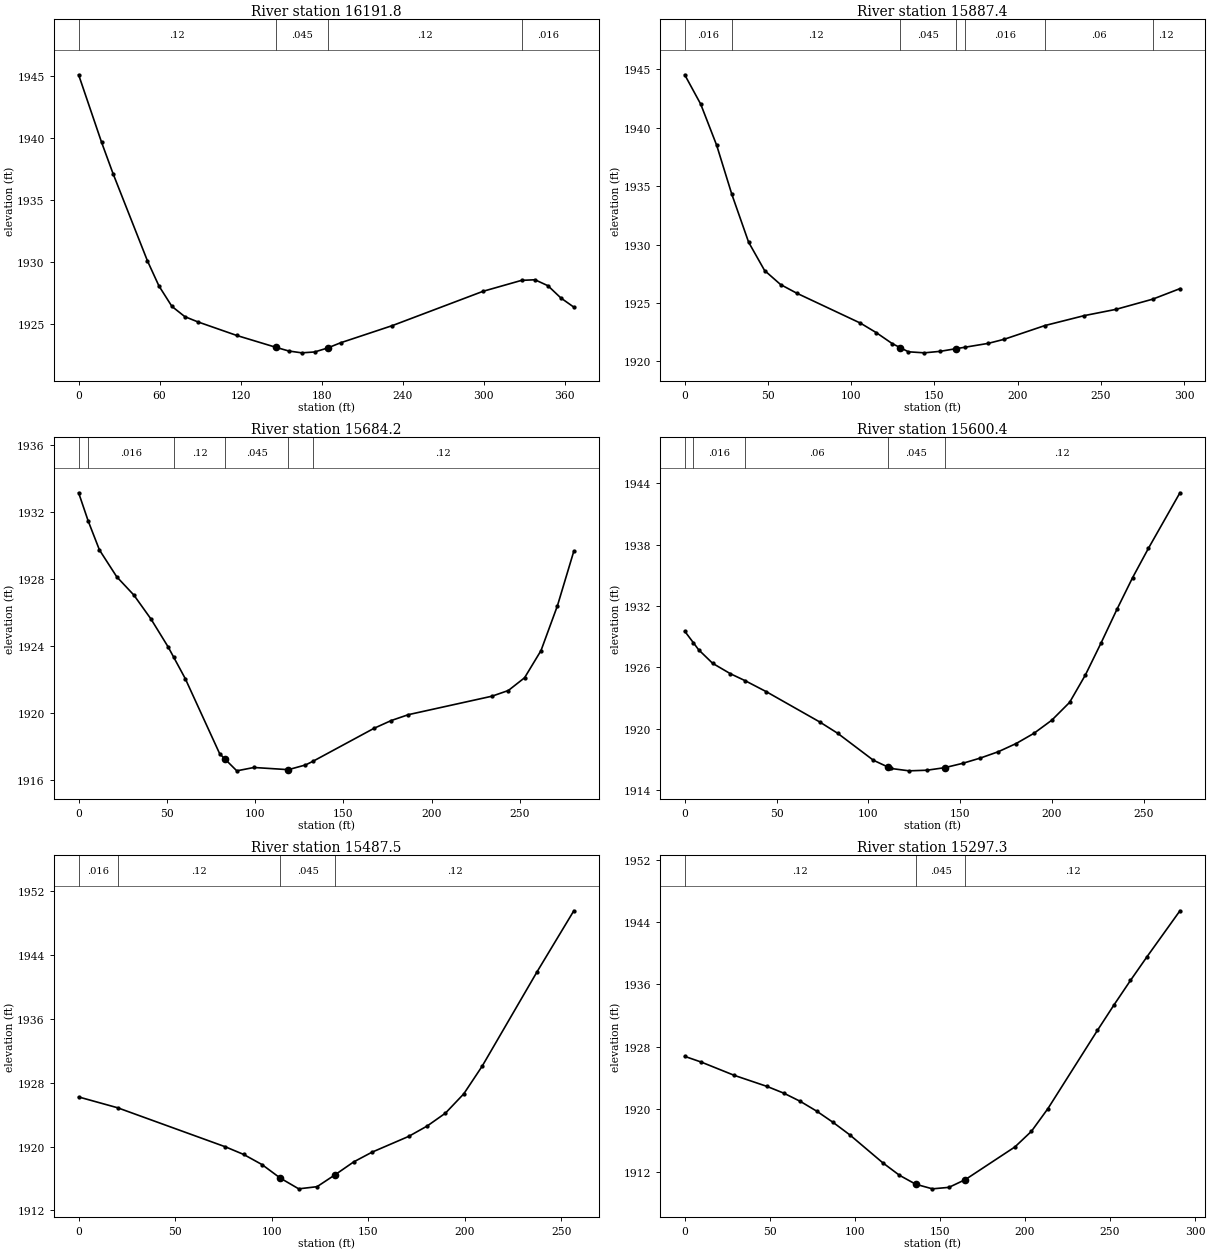
Type RM Length L Ch R = 1 ,16191.8 ,314.2,304.4,294.1
XS GIS Cut Line= 3
     1829098.793      182146.215     1829039.268        182146.3
     1828780.963      181979.807
#Sta/Elev= 22
       0 1945.09      17 1939.64    25.5 1937.11      51 1930.06    59.5 1928.04
    69.1 1926.39    78.7 1925.56    88.3 1925.14   117.2 1924.04     146 1923.09
   155.6 1922.79   165.2 1922.64   174.8 1922.71   184.4 1923.03     194 1923.45
   232.4 1924.84   299.6 1927.61  328.071928.491     338 1928.54   347.6 1928.06
   357.2 1927.07   366.8 1926.33
#Mann= 4 ,-1 , 0
       0     .12       0     146    .045       0   184.4     .12       0
  328.07    .016       0
Bank Sta=146,184.4
XS Rating Curve= 0 ,0
Exp/Cntr=0.3,0.1

Type RM Length L Ch R = 1 ,15887.4 ,221.9,203.2,183.9
XS GIS Cut Line= 2
     1829140.303      181901.214     1828862.371      181794.796
#Sta/Elev= 24
       0 1944.52     9.6 1942.01    19.2 1938.49   28.311934.296    38.4  1930.2
      48 1927.78    57.6 1926.58    67.2 1925.85   105.6 1923.28   115.2 1922.46
   124.8 1921.52   129.6 1921.18   134.4 1920.83     144 1920.74   153.6 1920.87
   163.2  1921.1  168.411921.219   182.4 1921.55     192  1921.9   216.51923.076
     240 1923.92   259.2 1924.46  281.231925.331   297.6 1926.23
#Mann= 7 ,-1 , 0
       0    .016       0   28.31     .12       0   129.6    .045       0
   163.2     .12       0  168.41    .016       0   216.5     .06       0
  281.23     .12       0
Bank Sta=129.6,163.2
XS Rating Curve= 0 ,0
Exp/Cntr=0.3,0.1

Type RM Length L Ch R = 1 ,15684.2 ,82.5,83.7,84.3
XS GIS Cut Line= 4
     1829171.169      181680.703     1829160.146      181676.362
     1828967.004      181698.498     1828896.621      181674.959
#Sta/Elev= 25
       0 1933.13    5.45 1931.44    11.8 1929.72    21.6 1928.12    31.3 1927.03
      41  1925.6    50.7 1923.94   53.941923.309    60.4 1922.05    79.9 1917.57
      83 1917.24    89.6 1916.55    99.3 1916.75   118.8 1916.62   128.5  1916.9
  132.721917.118   167.4 1919.09   177.1 1919.55   186.8  1919.9   234.1    1921
   243.4 1921.34   252.6  1922.1   261.9 1923.72   271.2 1926.39   280.5 1929.65
#Mann= 6 ,-1 , 0
       0     .12       0    5.45    .016       0   53.94     .12       0
      83    .045       0   118.8    .016       0  132.72     .12       0
Bank Sta=83,118.8
XS Rating Curve= 0 ,0
Exp/Cntr=0.3,0.1

Type RM Length L Ch R = 1 ,15600.4 ,109.5,112.9,116.8
XS GIS Cut Line= 4
      1829178.65      181599.909     1829164.486      181594.331
     1828971.344      181616.466     1828914.415      181597.427
#Sta/Elev= 28
       0 1929.54    4.72 1928.41     7.6 1927.72    15.2  1926.4    24.9 1925.38
   32.891924.703    44.4 1923.63    73.5 1920.67    83.3 1919.56   102.7 1916.93
   110.7 1916.26   112.4 1916.12   122.2 1915.89   131.9 1915.95   141.6  1916.2
   151.3 1916.62     161 1917.14   170.8 1917.76   180.5 1918.56   190.2 1919.56
   199.9 1920.84   209.6 1922.58   218.2 1925.26   226.8 1928.41   235.4 1931.68
   243.9 1934.77   252.5 1937.63   269.7 1943.07
#Mann= 5 ,-1 , 0
       0     .12       0    4.72    .016       0   32.89     .06       0
   110.7    .045       0   141.6     .12       0
Bank Sta=110.7,141.6
XS Rating Curve= 0 ,0
Exp/Cntr=0.3,0.1

Type RM Length L Ch R = 1 ,15487.5 ,199.8,190.2,181.2
XS GIS Cut Line= 2
     1829174.027       181495.59     1828917.525       181495.59
#Sta/Elev= 18
       0 1926.23   20.211924.873      76 1919.98    85.5 1919.02      95 1917.75
   104.5 1916.05     114 1914.71   123.5 1914.98     133  1916.5   142.5 1918.09
     152 1919.31     171 1921.29   180.5 1922.58     190  1924.2   199.5 1926.62
     209 1930.08   237.5 1941.94   256.5 1949.57
#Mann= 4 ,-1 , 0
       0    .016       0   20.21     .12       0   104.5    .045       0
     133     .12       0
Bank Sta=104.5,133
XS Rating Curve= 0 ,0
Exp/Cntr=0.3,0.1

Type RM Length L Ch R = 1 ,15297.3 ,273.1,284.4,294.9
XS GIS Cut Line= 2
      1829154.53      181276.326     1828876.357      181362.145
#Sta/Elev= 23
       0 1926.79     9.7 1926.06    29.1 1924.36    48.5 1922.93    58.2 1922.08
    67.9 1921.03    77.6 1919.77    87.3 1918.32      97 1916.74   116.4 1913.16
   126.2 1911.56   135.8 1910.41   145.6 1909.82   155.3 1910.01     165 1911.01
   194.1 1915.19   203.8 1917.19   213.5  1920.1   242.6 1930.12   252.3 1933.37
     262 1936.51   271.7 1939.54   291.1 1945.44
#Mann= 3 ,-1 , 0
       0     .12       0   135.8    .045       0     165     .12       0
Bank Sta=135.8,165
XS Rating Curve= 0 ,0
Exp/Cntr=0.3,0.1

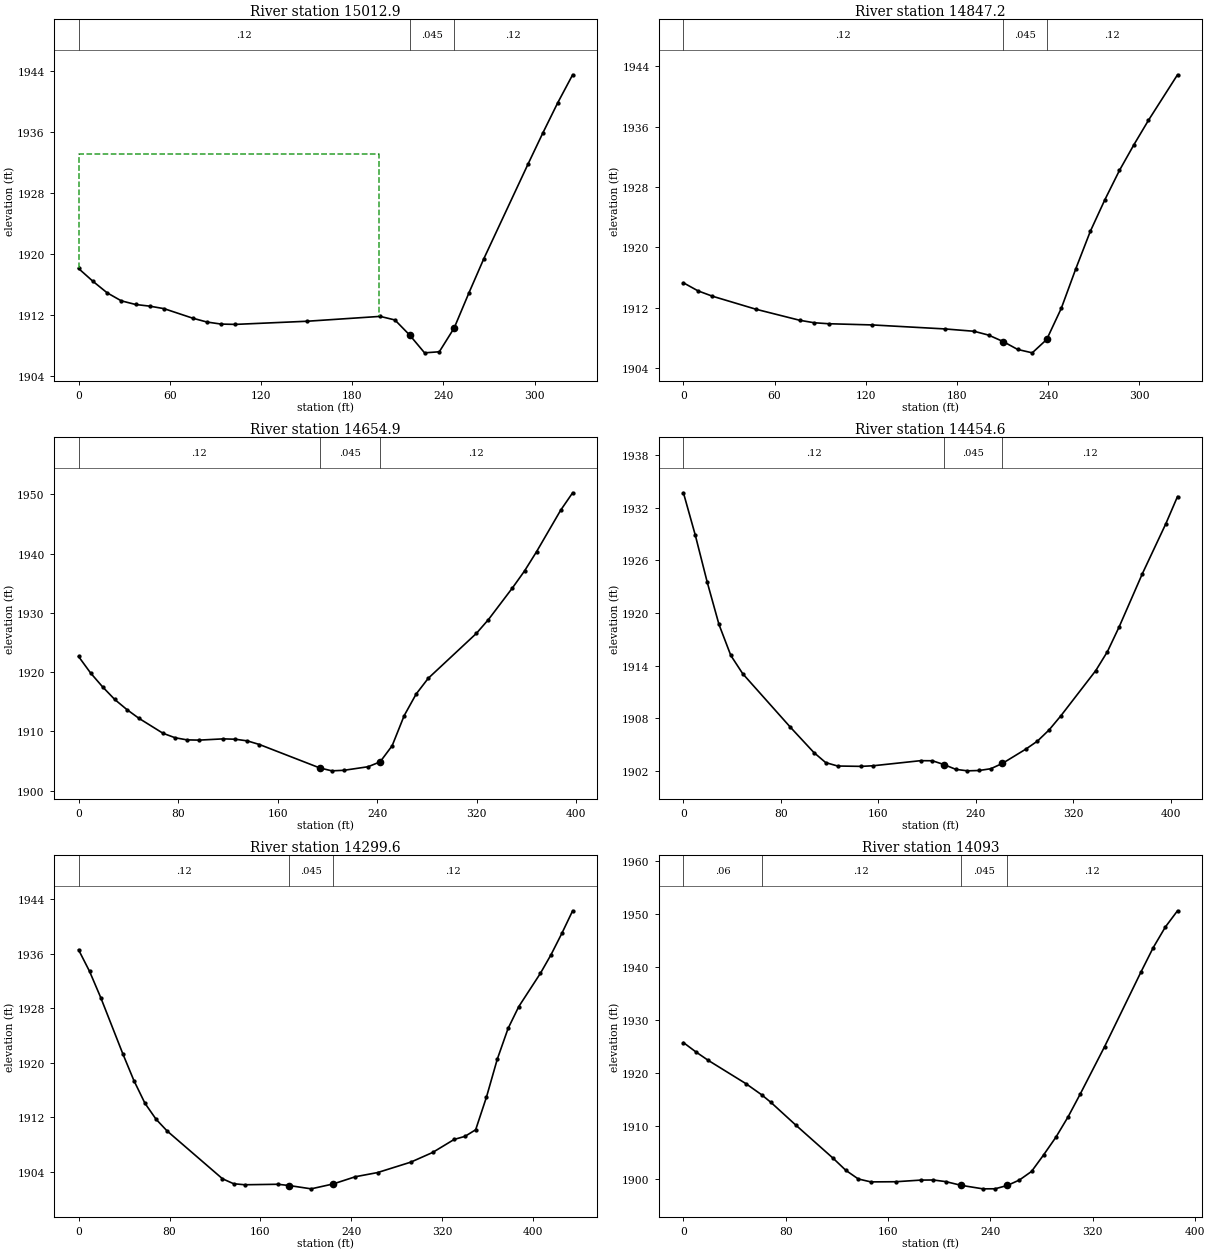
Type RM Length L Ch R = 1 ,15012.9 ,145,165.7,186.3
XS GIS Cut Line= 3
     1829164.898      181107.903     1829011.924      181062.967
     1828846.556      181056.117
#Sta/Elev= 24
       0 1918.12     9.4 1916.45    18.8 1914.93    28.1 1913.88    37.5  1913.4
    46.9 1913.18    56.3 1912.85      75 1911.61    84.4  1911.1    93.8 1910.83
   103.2 1910.79   150.1  1911.2   198.4 1911.84   208.1 1911.37   217.8 1909.39
   227.6 1907.06   237.3  1907.2   247.1 1910.33   256.8 1914.93   266.5 1919.37
   295.7 1931.83   305.5 1935.93   315.2 1939.85     325 1943.52
#Mann= 3 ,-1 , 0
       0     .12       0   217.8    .045       0   247.1     .12       0
#XS Ineff= 2 , 0
          197.85 1933.15
Permanent Ineff=
       F       F
Bank Sta=217.8,247.1
XS Rating Curve= 0 ,0
Exp/Cntr=0.3,0.1

Type RM Length L Ch R = 1 ,14847.2 ,187.2,192.3,185.5
XS GIS Cut Line= 2
     1829176.422       181031.18     1828906.332      180850.022
#Sta/Elev= 23
       0 1915.28     9.6 1914.21    19.1  1913.5    47.8 1911.77    76.5 1910.31
    86.1 1909.98    95.6 1909.85   124.4 1909.69   172.2 1909.16   191.3 1908.85
   200.9 1908.34   210.4 1907.49     220 1906.44   229.6 1905.99   239.1 1907.76
   248.7 1911.89   258.3 1917.16   267.8  1922.1   277.4  1926.3     287 1930.19
   296.5 1933.59   306.1 1936.84   325.2 1942.87
#Mann= 3 ,-1 , 0
       0     .12       0   210.4    .045       0   239.1     .12       0
Bank Sta=210.4,239.1
XS Rating Curve= 0 ,0
Exp/Cntr=0.3,0.1

Type RM Length L Ch R = 1 ,14654.9 ,199,200.3,213.4
XS GIS Cut Line= 3
     1829291.465       180918.47     1829095.556      180744.876
     1828960.162      180740.219
#Sta/Elev= 30
       0 1922.64     9.7 1919.85    19.4  1917.5    29.1 1915.39    38.8  1913.7
    48.5 1912.22    67.9 1909.69    77.6 1908.94    87.2 1908.58      97 1908.54
   116.3 1908.75     126 1908.69   135.7 1908.41   145.4  1907.8   193.9 1903.85
   203.6 1903.36   213.3 1903.45   232.7 1904.05   242.4 1904.87   252.1 1907.59
   261.8 1912.68   271.4 1916.31   281.1 1918.96   319.8 1926.53   329.5 1928.86
   348.8  1934.2   358.5 1937.05   368.2 1940.31   387.6 1947.31   397.2 1950.24
#Mann= 3 ,-1 , 0
       0     .12       0   193.9    .045       0   242.4     .12       0
Bank Sta=193.9,242.4
XS Rating Curve= 0 ,0
Exp/Cntr=0.3,0.1

Type RM Length L Ch R = 1 ,14454.6 ,153.5,155,156.5
XS GIS Cut Line= 3
     1829422.617      180778.061     1829273.964      180637.694
     1829127.982       180499.36
#Sta/Elev= 30
       0 1933.72     9.7 1928.91    19.5 1923.54    29.2 1918.69    38.9 1915.16
    48.7 1913.07    87.6    1907   107.1 1904.08   116.8 1902.93   126.6 1902.54
     146  1902.5   155.8 1902.57   194.7 1903.15   204.4 1903.14     214  1902.7
   223.6 1902.16   233.2 1901.99   242.8 1902.03   252.3 1902.23   261.9 1902.84
   281.1 1904.47   290.6 1905.38   300.2 1906.66   309.8 1908.26   338.5 1913.43
   348.1  1915.6   357.7 1918.42   376.8  1924.5     396 1930.18   405.6 1933.29
#Mann= 3 ,-1 , 0
       0     .12       0     214    .045       0   261.9     .12       0
Bank Sta=214,261.9
XS Rating Curve= 0 ,0
Exp/Cntr=0.3,0.1

Type RM Length L Ch R = 1 ,14299.6 ,205.4,206.7,204.3
XS GIS Cut Line= 3
     1829517.812      180672.776     1829307.933      180455.659
     1829278.663      180326.305
#Sta/Elev= 30
       0 1936.58     9.7  1933.4    19.5 1929.56      39 1921.27    48.7 1917.36
    58.4 1914.03    68.2 1911.68    77.9 1909.96   126.6 1902.94   136.4 1902.21
   146.1 1902.06   175.3 1902.13   185.1 1901.95   204.6 1901.46     224 1902.18
   243.5 1903.24     263 1903.85   292.2 1905.38   311.4  1906.8   330.4 1908.72
   339.9 1909.17   349.3 1910.14   358.8 1914.94   368.3  1920.5   377.8 1925.02
   387.2 1928.23   406.2 1933.11   415.6 1935.86   425.1 1938.99   434.6 1942.31
#Mann= 3 ,-1 , 0
       0     .12       0   185.1    .045       0     224     .12       0
Bank Sta=185.1,224
XS Rating Curve= 0 ,0
Exp/Cntr=0.3,0.1

Type RM Length L Ch R = 1 ,14093   ,185.9,171,155.6
XS GIS Cut Line= 3
     1829640.423      180531.433     1829480.385      180373.834
     1829366.614      180259.065
#Sta/Elev= 30
       0 1925.72     9.8 1923.95    19.5 1922.35    48.8 1917.98   61.081915.882
    68.4 1914.44    87.9 1910.14   117.2 1903.86     127 1901.61   136.7 1899.99
   146.5 1899.44     166 1899.47   185.6 1899.78   195.3  1899.8   205.1 1899.49
   217.1 1898.79   234.1 1898.13   243.6 1898.14   253.1 1898.76   262.6 1899.79
   272.1 1901.41   281.6 1904.55   291.2 1907.89   300.7 1911.72   310.2 1916.03
   329.2 1924.95   357.7 1939.06   367.2 1943.62   376.7 1947.52   386.2 1950.58
#Mann= 4 ,-1 , 0
       0     .06       0   61.08     .12       0   217.1    .045       0
   253.1     .12       0
Bank Sta=217.1,253.1
XS Rating Curve= 0 ,0
Exp/Cntr=0.3,0.1

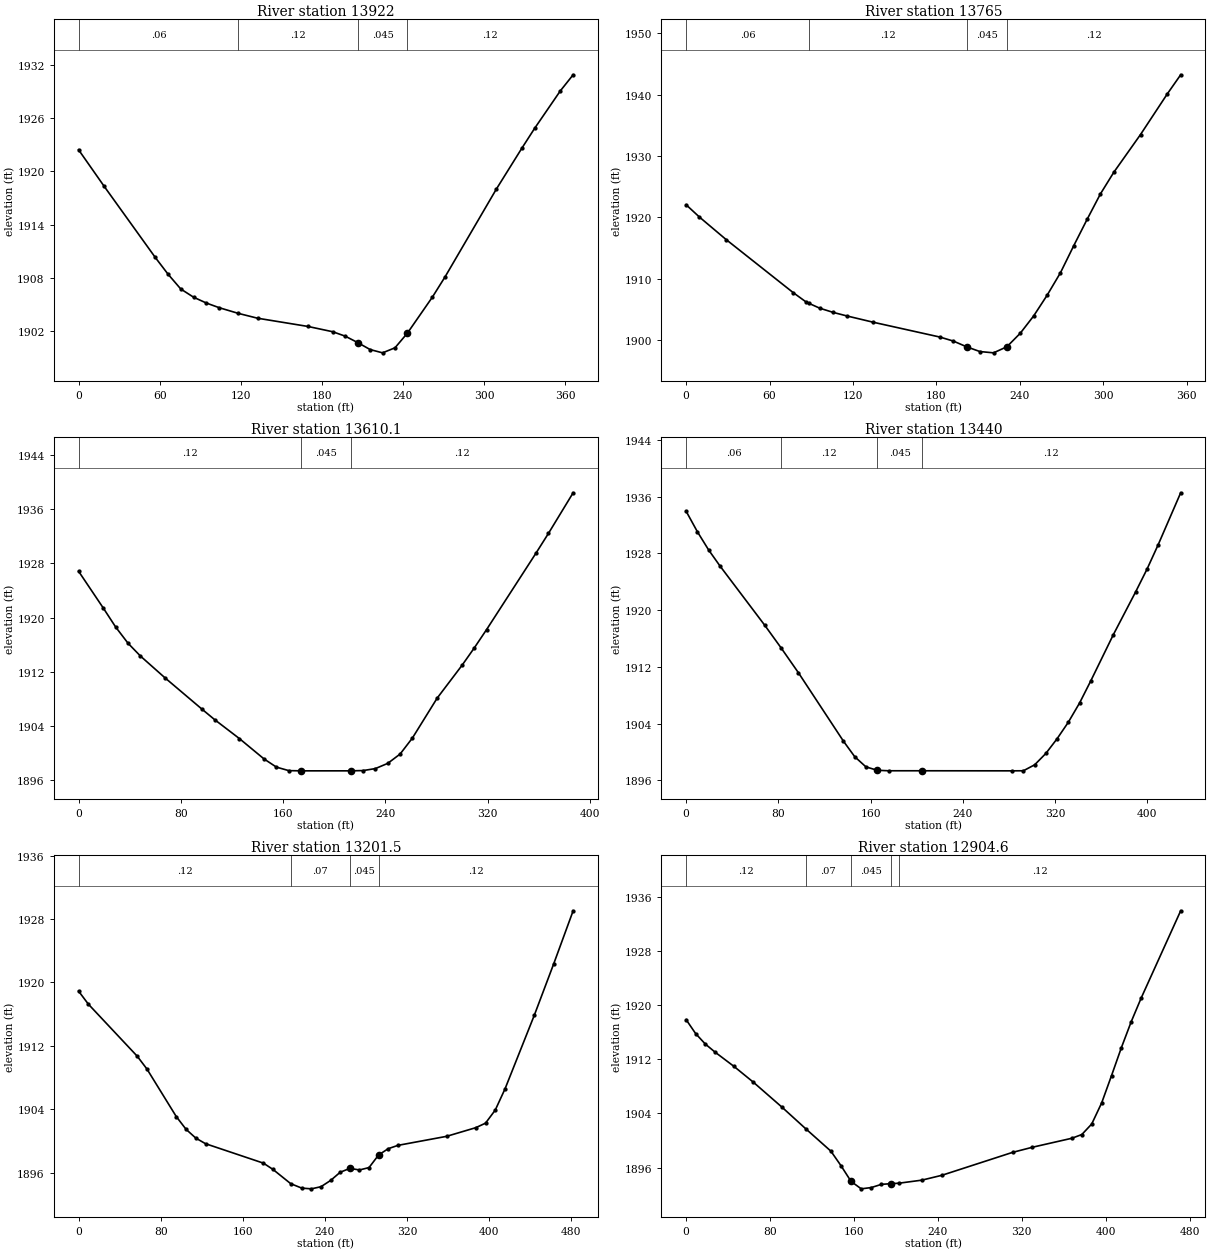
Type RM Length L Ch R = 1 ,13922   ,133.5,157,178.8
XS GIS Cut Line= 4
      1829754.15      180396.307     1829653.851      180283.019
     1829549.684      180246.561     1829473.297      180175.711
#Sta/Elev= 25
       0 1922.45    18.9 1918.33    56.7  1910.3    66.2  1908.4    75.6 1906.73
    85.1  1905.8    94.6 1905.14     104 1904.62   118.21903.975   132.4 1903.43
   169.7  1902.5   188.1  1901.9   197.3  1901.4   206.5 1900.68   215.7 1899.89
   224.9 1899.52   234.1 1900.09   243.3 1901.75   261.7  1905.8   271.1 1908.09
     309 1917.99     328 1922.64   337.4 1924.87   356.4  1929.1   365.9 1930.92
#Mann= 4 ,-1 , 0
       0     .06       0   118.2     .12       0   206.5    .045       0
   243.3     .12       0
Bank Sta=206.5,243.3
XS Rating Curve= 0 ,0
Exp/Cntr=0.3,0.1

Type RM Length L Ch R = 1 ,13765   ,157.7,154.8,154.1
XS GIS Cut Line= 2
     1829814.081      180329.091      1829603.61      180042.377
#Sta/Elev= 27
       0 1922.06     9.6 1920.05    28.8 1916.38    76.9 1907.75    86.5 1906.17
   88.581905.958    96.1 1905.19   105.7 1904.51   115.4 1903.94   134.6  1902.9
   182.6 1900.48   192.3 1899.82   201.9 1898.88   211.3 1898.12   221.1 1897.91
   230.7  1898.9   240.3  1901.1   249.9 1903.91   259.6 1907.29   269.2 1910.96
   278.8 1915.39   288.4 1919.68     298 1923.84   307.6 1927.36   326.8 1933.51
   346.1 1940.15   355.7 1943.26
#Mann= 4 ,-1 , 0
       0     .06       0   88.58     .12       0   201.9    .045       0
   230.7     .12       0
Bank Sta=201.9,230.7
XS Rating Curve= 0 ,0
Exp/Cntr=0.3,0.1

Type RM Length L Ch R = 1 ,13610.1 ,158,170.2,173.5
XS GIS Cut Line= 2
      1829928.15      180266.194     1829713.461       179944.16
#Sta/Elev= 26
       0 1926.83    19.4 1921.38      29  1918.6    38.7  1916.2    48.4 1914.31
    67.7 1911.08    96.8 1906.43   106.4 1904.93   125.8 1902.13   145.1 1899.12
   154.8 1897.91   164.5 1897.39   174.2 1897.36   212.9 1897.36   222.6  1897.4
   232.2 1897.69   241.9 1898.46   251.6 1899.84   261.2  1902.2   280.6  1908.1
     300 1912.93   309.6  1915.5   319.3 1918.23     358 1929.53   367.7 1932.43
     387 1938.42
#Mann= 3 ,-1 , 0
       0     .12       0   174.2    .045       0   212.9     .12       0
Bank Sta=174.2,212.9
XS Rating Curve= 0 ,0
Exp/Cntr=0.3,0.1

Type RM Length L Ch R = 1 ,13440   ,233.1,238.4,256.7
XS GIS Cut Line= 2
     1830064.753      180211.535     1829854.774      179837.279
#Sta/Elev= 26
       0 1933.94     9.8 1931.04    19.5 1928.49    29.3 1926.24    68.3 1917.85
   82.591914.636    97.5 1911.16   136.5 1901.53   146.3 1899.34     156 1897.91
   165.8 1897.43   175.6 1897.36   204.8 1897.36   282.8 1897.35   292.6 1897.36
   302.4  1898.2   312.1  1899.8   321.8 1901.86   331.6  1904.2   341.4 1906.92
   351.1 1910.03   370.6 1916.52   390.1  1922.6   399.9 1925.78   409.6 1929.23
   429.1 1936.54
#Mann= 4 ,-1 , 0
       0     .06       0   82.59     .12       0   165.8    .045       0
   204.8     .12       0
Bank Sta=165.8,204.8
XS Rating Curve= 0 ,0
Exp/Cntr=0.3,0.1

Type RM Length L Ch R = 1 ,13201.5 ,325.3,296.9,242.3
XS GIS Cut Line= 4
     1830213.728      180122.899      1830203.33       179990.05
     1830073.999      179867.971     1829946.391      179754.418
#Sta/Elev= 30
       0  1918.9     9.5 1917.26    57.1  1910.7    66.6 1909.08    95.2 1903.08
   104.7 1901.48   114.2 1900.37   123.7 1899.66   180.1 1897.21   189.4 1896.42
   206.71894.621   217.5 1894.06   226.9 1893.97   236.2 1894.24   245.6 1895.03
   254.9 1896.06   264.3 1896.55   273.7 1896.35     283 1896.65   292.4 1898.25
   301.7 1899.03   311.1 1899.45   358.6 1900.59     387 1901.68   396.5 1902.25
     406  1903.9   415.5 1906.57     444 1915.84   462.9 1922.32   481.9 1929.03
#Mann= 4 ,-1 , 0
       0     .12       0   206.7     .07       0   264.3    .045       0
   292.4     .12       0
Bank Sta=264.3,292.4
XS Rating Curve= 0 ,0
Exp/Cntr=0.3,0.1

Type RM Length L Ch R = 1 ,12904.6 ,291.6,292.7,289.2
XS GIS Cut Line= 4
     1830457.164      179704.565     1830342.653      179736.144
      1830140.83      179729.633     1830004.655       179665.08
#Sta/Elev= 29
       0 1917.85     9.1 1915.79    18.3 1914.25    27.4 1913.08    45.7 1910.94
      64 1908.63    91.4 1904.93  113.861901.768     138 1898.44   147.6  1896.3
   157.2 1893.98   166.9 1892.88   176.5 1893.07   186.1 1893.54   195.7 1893.65
  202.571893.707   224.6 1894.16   243.8 1894.88   311.1 1898.26   330.1 1899.02
   367.8 1900.35   377.2  1900.9   386.6 1902.45   396.1 1905.57   405.5  1909.6
   414.9 1913.73   424.3 1917.57   433.7 1921.03   471.4 1933.92
#Mann= 5 ,-1 , 0
       0     .12       0  113.86     .07       0   157.2    .045       0
   195.7     .07       0  202.57     .12       0
Bank Sta=157.2,195.7
XS Rating Curve= 0 ,0
Exp/Cntr=0.3,0.1

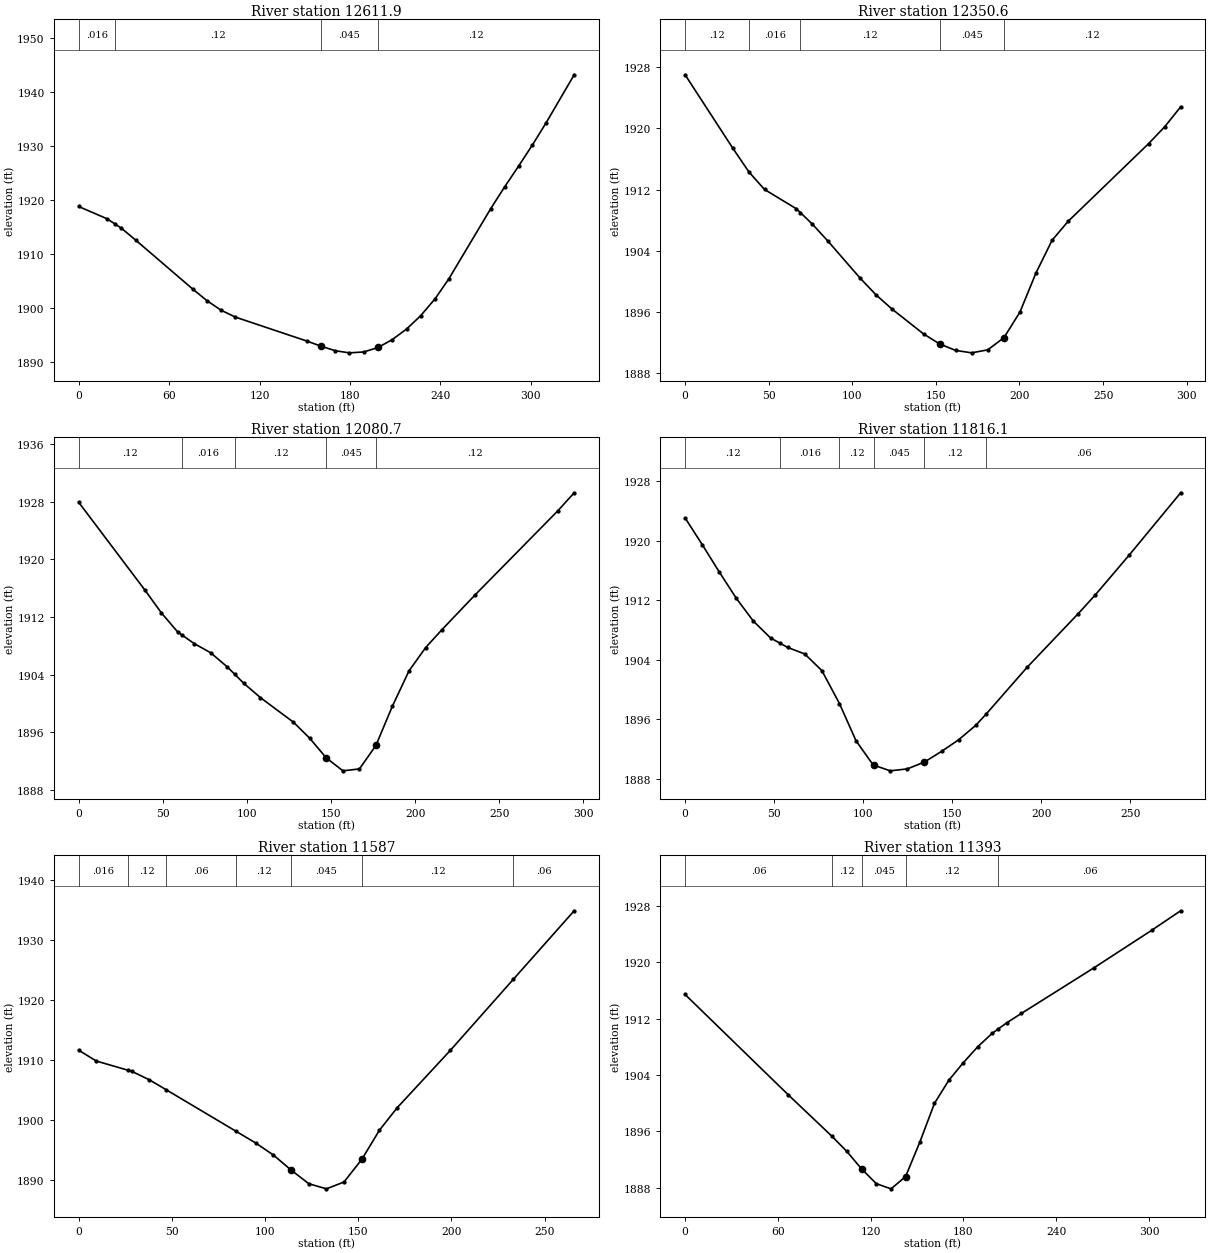
Type RM Length L Ch R = 1 ,12611.9 ,266,261.3,262
XS GIS Cut Line= 3
     1830413.073      179478.071     1830176.856      179469.548
     1830086.988       179448.54
#Sta/Elev= 26
       0 1918.73    18.9 1916.45   23.981915.514    28.4  1914.7    37.8 1912.51
    75.6 1903.45    85.1 1901.28    94.6 1899.49     104 1898.23   151.3  1893.8
   160.7 1892.85   170.2    1892   179.6 1891.61   189.1 1891.77   198.6  1892.6
     208 1894.06   217.5 1896.01   226.9  1898.5   236.4 1901.61   245.6 1905.34
   273.3 1918.31   282.5 1922.33   291.8  1926.2     301 1930.13   310.2 1934.29
   328.7 1943.14
#Mann= 4 ,-1 , 0
       0    .016       0   23.98     .12       0   160.7    .045       0
   198.6     .12       0
Bank Sta=160.7,198.6
XS Rating Curve= 0 ,0
Exp/Cntr=0.3,0.1

Type RM Length L Ch R = 1 ,12350.6 ,266,269.9,255.7
XS GIS Cut Line= 3
     1830428.233      179278.088     1830289.349      179245.705
     1830140.201       179208.32
#Sta/Elev= 24
       0 1927.03    28.5 1917.43   38.211914.308    47.5 1912.02    66.6 1909.49
   68.951908.995    76.1 1907.49    85.6 1905.22   104.6 1900.44   114.1 1898.25
   123.6  1896.4   142.6 1893.12   152.2 1891.81   161.8 1890.96   171.4 1890.64
     181 1891.03   190.7 1892.62   200.3 1895.98   209.9 1901.11   219.5 1905.37
   229.1 1907.85   277.2 1918.01   286.8 1920.21   296.4 1922.83
#Mann= 5 ,-1 , 0
       0     .12       0   38.21    .016       0   68.95     .12       0
   152.2    .045       0   190.7     .12       0
Bank Sta=152.2,190.7
XS Rating Curve= 0 ,0
Exp/Cntr=0.3,0.1

Type RM Length L Ch R = 1 ,12080.7 ,267.7,264.6,256
XS GIS Cut Line= 2
     1830444.685      179037.482     1830150.422      179025.582
#Sta/Elev= 24
       0 1927.95    39.3 1915.77    49.1  1912.6    58.9 1909.91   61.441909.495
    68.7 1908.31    78.5 1907.03    88.4 1905.06   92.891904.015    98.2 1902.78
     108 1900.81   127.6  1897.4   137.4 1895.14   147.2 1892.42   157.1 1890.63
   166.9  1890.9   176.7 1894.17   186.5 1899.63   196.3  1904.5   206.2 1907.75
     216 1910.26   235.6 1915.07   284.7 1926.73   294.5 1929.26
#Mann= 5 ,-1 , 0
       0     .12       0   61.44    .016       0   92.89     .12       0
   147.2    .045       0   176.7     .12       0
Bank Sta=147.2,176.7
XS Rating Curve= 0 ,0
Exp/Cntr=0.3,0.1

Type RM Length L Ch R = 1 ,11816.1 ,239.4,229.2,222
XS GIS Cut Line= 2
      1830428.72      178788.268     1830150.422       178792.16
#Sta/Elev= 26
       0 1923.09     9.6 1919.51    19.2 1915.82    28.8 1912.27    38.4  1909.2
      48 1906.95   53.541906.217    57.6 1905.68    67.2  1904.8    76.8 1902.57
   86.691898.134      96 1893.13   105.6 1889.89   105.9 1889.86   115.2 1889.09
   124.8 1889.35   134.4 1890.27     144  1891.7   153.6 1893.26   163.2  1895.2
  169.221896.761     192 1902.99   220.7  1910.2   230.3 1912.72   249.5 1918.12
   278.3 1926.47
#Mann= 6 ,-1 , 0
       0     .12       0   53.54    .016       0   86.69     .12       0
   105.9    .045       0   134.4     .12       0  169.22     .06       0
Bank Sta=105.9,134.4
XS Rating Curve= 0 ,0
Exp/Cntr=0.3,0.1

Type RM Length L Ch R = 1 ,11587   ,181.1,194,203.4
XS GIS Cut Line= 2
     1830362.452       178541.24     1830107.867      178618.019
#Sta/Elev= 19
       0 1911.61     9.5  1909.8   26.371908.281    28.5 1908.09      38 1906.67
   46.851905.049   84.591898.086      95 1896.16   104.5 1894.16     114 1891.66
   123.5 1889.38     133 1888.53   142.4 1889.67     152 1893.46   161.4 1898.28
   170.9 1902.02   199.4 1911.56  233.341923.434   265.9 1934.81
#Mann= 7 ,-1 , 0
       0    .016       0   26.37     .12       0   46.85     .06       0
   84.59     .12       0     114    .045       0     152     .12       0
  233.34     .06       0
Bank Sta=114,152
XS Rating Curve= 0 ,0
Exp/Cntr=0.3,0.1

Type RM Length L Ch R = 1 ,11393   ,209.1,224.6,243.4
XS GIS Cut Line= 3
     1830326.947      178399.456     1830193.924      178392.805
     1830006.815      178400.758
#Sta/Elev= 20
       0 1915.41    66.6 1901.19   95.031895.264   104.6 1893.12   114.2 1890.63
   123.7 1888.54   133.2 1887.81   142.6 1889.55   151.9 1894.49   161.3 1899.96
   170.6 1903.24     180 1905.74   189.4 1908.02   198.7 1909.91  202.581910.525
   208.1  1911.4   217.5 1912.72   264.3 1919.18   301.7 1924.52   320.5  1927.3
#Mann= 5 ,-1 , 0
       0     .06       0   95.03     .12       0   114.2    .045       0
   142.6     .12       0  202.58     .06       0
Bank Sta=114.2,142.6
XS Rating Curve= 0 ,0
Exp/Cntr=0.3,0.1

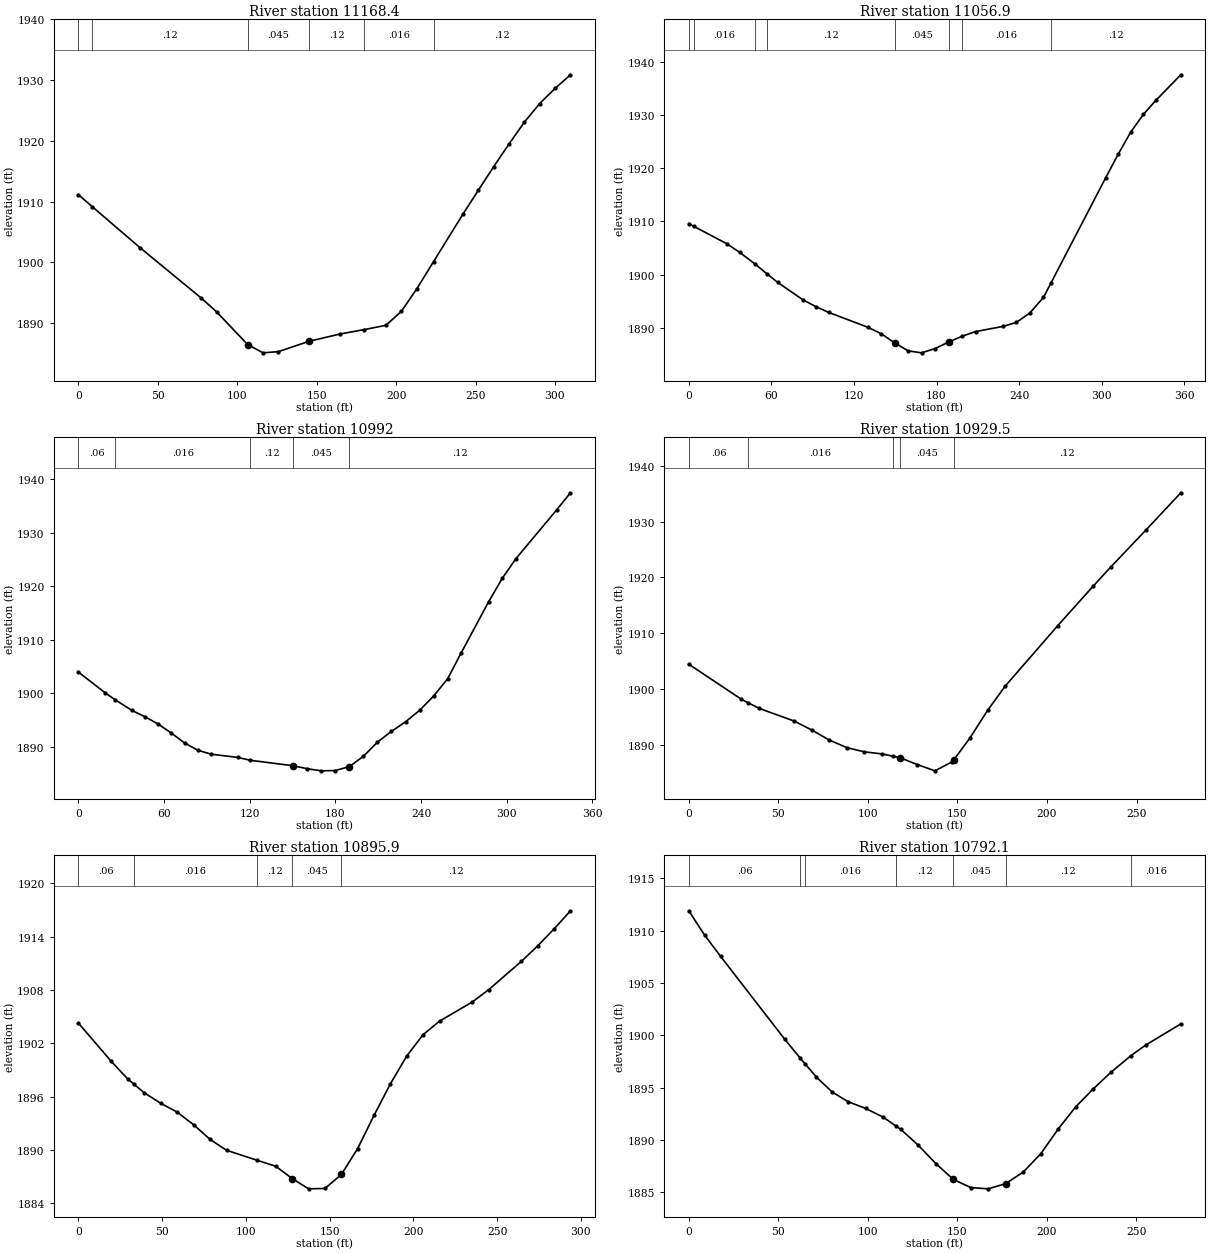
Type RM Length L Ch R = 1 ,11168.4 ,138.2,111.4,84.7
XS GIS Cut Line= 2
     1830339.617      178228.446     1830061.397      178092.175
#Sta/Elev= 23
       0 1911.13    8.661909.175    38.7 1902.44    77.4 1894.12    87.1 1891.84
   106.5  1886.5   116.2 1885.13   125.9 1885.33   145.2 1887.03   164.6 1888.22
  179.941888.953   193.6 1889.66   203.3 1891.95     213 1895.65  223.621900.149
     242  1907.9   251.7 1911.84   261.4 1915.73   271.1 1919.49   280.8 1923.08
   290.4 1926.13   300.1 1928.63   309.8 1930.86
#Mann= 6 ,-1 , 0
       0    .016       0    8.66     .12       0   106.5    .045       0
   145.2     .12       0  179.94    .016       0  223.62     .12       0
Bank Sta=106.5,145.2
XS Rating Curve= 0 ,0
Exp/Cntr=0.3,0.1

Type RM Length L Ch R = 1 ,11056.9 ,74.1,65,58.9
XS GIS Cut Line= 4
      1830393.87      178144.481     1830307.716      178060.911
     1830174.252      178094.548     1830095.141      178033.687
#Sta/Elev= 30
       0 1909.56    3.481909.076    27.7 1905.78    36.9 1904.18   47.88 1902.03
   56.581900.176    64.6 1898.52    83.1 1895.23    92.3 1893.98   101.6 1892.89
   129.9 1890.12   139.7 1888.89   149.5 1887.19   159.4 1885.66   169.2 1885.29
     179  1886.1   188.8 1887.32   198.61888.419   208.5 1889.29   228.2 1890.25
     238    1891   247.8 1892.78   257.7  1895.7  263.061898.368     303 1918.22
   312.1 1922.66   321.2 1926.79   330.3 1930.08   339.3  1932.7   357.5 1937.53
#Mann= 8 ,-1 , 0
       0     .06       0    3.48    .016       0   47.88     .06       0
   56.58     .12       0   149.5    .045       0   188.8     .12       0
   198.6    .016       0  263.06     .12       0
Bank Sta=149.5,188.8
XS Rating Curve= 0 ,0
Exp/Cntr=0.3,0.1

Type RM Length L Ch R = 1 ,10992   ,12.4,62.5,108.9
XS GIS Cut Line= 4
     1830415.571       178081.31     1830328.766      177997.109
     1830195.302      178030.746     1830127.105      177978.281
#Sta/Elev= 30
       0 1903.96    18.6 1900.11   25.511898.825    37.2 1896.83    46.5 1895.62
    55.8 1894.25    65.1 1892.55    74.4 1890.69    83.7 1889.35      93 1888.61
   111.6 1888.01  120.381887.472   150.4 1886.45   160.3 1885.89   170.1  1885.5
   179.9 1885.56   189.8  1886.3   199.6 1888.22   209.4 1890.86   219.2 1892.88
   229.1 1894.67   238.9 1896.81   248.7 1899.47   258.6 1902.74   268.1 1907.58
   287.2 1917.08   296.8 1921.49   306.4 1925.18     335 1934.32   344.6 1937.49
#Mann= 5 ,-1 , 0
       0     .06       0   25.51    .016       0  120.38     .12       0
   150.4    .045       0   189.8     .12       0
Bank Sta=150.4,189.8
XS Rating Curve= 0 ,0
Exp/Cntr=0.3,0.1

Type RM Length L Ch R = 1 ,10929.5 ,9,33.6,66.7
XS GIS Cut Line= 2
     1830421.908      178075.321     1830230.936      177877.838
#Sta/Elev= 24
       0 1904.46    29.4 1898.17   33.061897.569    39.2 1896.56    58.9 1894.26
    68.7 1892.66    78.5 1890.86    88.3  1889.5    98.1 1888.75   107.9 1888.38
  114.08 1887.97   117.7 1887.73   127.6 1886.47   137.4 1885.35   147.2 1886.99
   147.9 1887.29     157 1891.25   166.8 1896.17   176.6 1900.51     206 1911.37
   225.7 1918.42   235.5 1921.85   255.1 1928.46   274.7 1935.18
#Mann= 5 ,-1 , 0
       0     .06       0   33.06    .016       0  114.08     .12       0
   117.7    .045       0   147.9     .12       0
Bank Sta=117.7,147.9
XS Rating Curve= 0 ,0
Exp/Cntr=0.3,0.1

Type RM Length L Ch R = 1 ,10895.9 ,85.2,103.8,114.5
XS GIS Cut Line= 3
     1830425.641      178067.421     1830350.988      177989.296
      1830354.46      177803.532
#Sta/Elev= 28
       0 1904.28    19.6 1899.97    29.5 1897.98    33.11897.414    39.3 1896.44
    49.1 1895.26    58.9 1894.27    68.8 1892.84    78.6 1891.19    88.4 1889.97
  106.561888.852   117.8 1888.17   127.6 1886.79   137.4 1885.63   147.2 1885.67
     157 1887.25   166.7 1890.16   176.5  1893.9   186.3 1897.46   196.1  1900.6
   205.8 1902.98   215.6  1904.5   235.2 1906.66     245 1908.05   264.5 1911.23
   274.3 1912.99   284.1  1914.9   293.8 1916.92
#Mann= 5 ,-1 , 0
       0     .06       0    33.1    .016       0  106.56     .12       0
   127.6    .045       0     157     .12       0
Bank Sta=127.6,157
XS Rating Curve= 0 ,0
Exp/Cntr=0.3,0.1

Type RM Length L Ch R = 1 ,10792.1 ,133.9,90.2,46.2
XS GIS Cut Line= 3
     1830489.147      178030.622     1830427.594      177966.206
     1830431.066      177780.442
#Sta/Elev= 28
       0 1911.91     8.9 1909.57    17.8 1907.55    53.5 1899.66   62.381897.804
   64.891897.302    71.3 1896.02    80.2 1894.58    89.1 1893.66    98.9 1893.02
   108.6 1892.19  115.571891.365   118.4 1891.03   128.2 1889.51     138 1887.76
   147.8 1886.24   157.6 1885.46   167.3 1885.34   177.1 1885.84   186.9 1886.95
   196.7  1888.7   206.4 1891.06   216.2 1893.18     226 1894.89   235.8 1896.47
  247.021898.064   255.3 1899.08   274.9  1901.1
#Mann= 7 ,-1 , 0
       0     .06       0   62.38     .12       0   64.89    .016       0
  115.57     .12       0   147.8    .045       0   177.1     .12       0
  247.02    .016       0
Bank Sta=147.8,177.1
XS Rating Curve= 0 ,0
Exp/Cntr=0.3,0.1

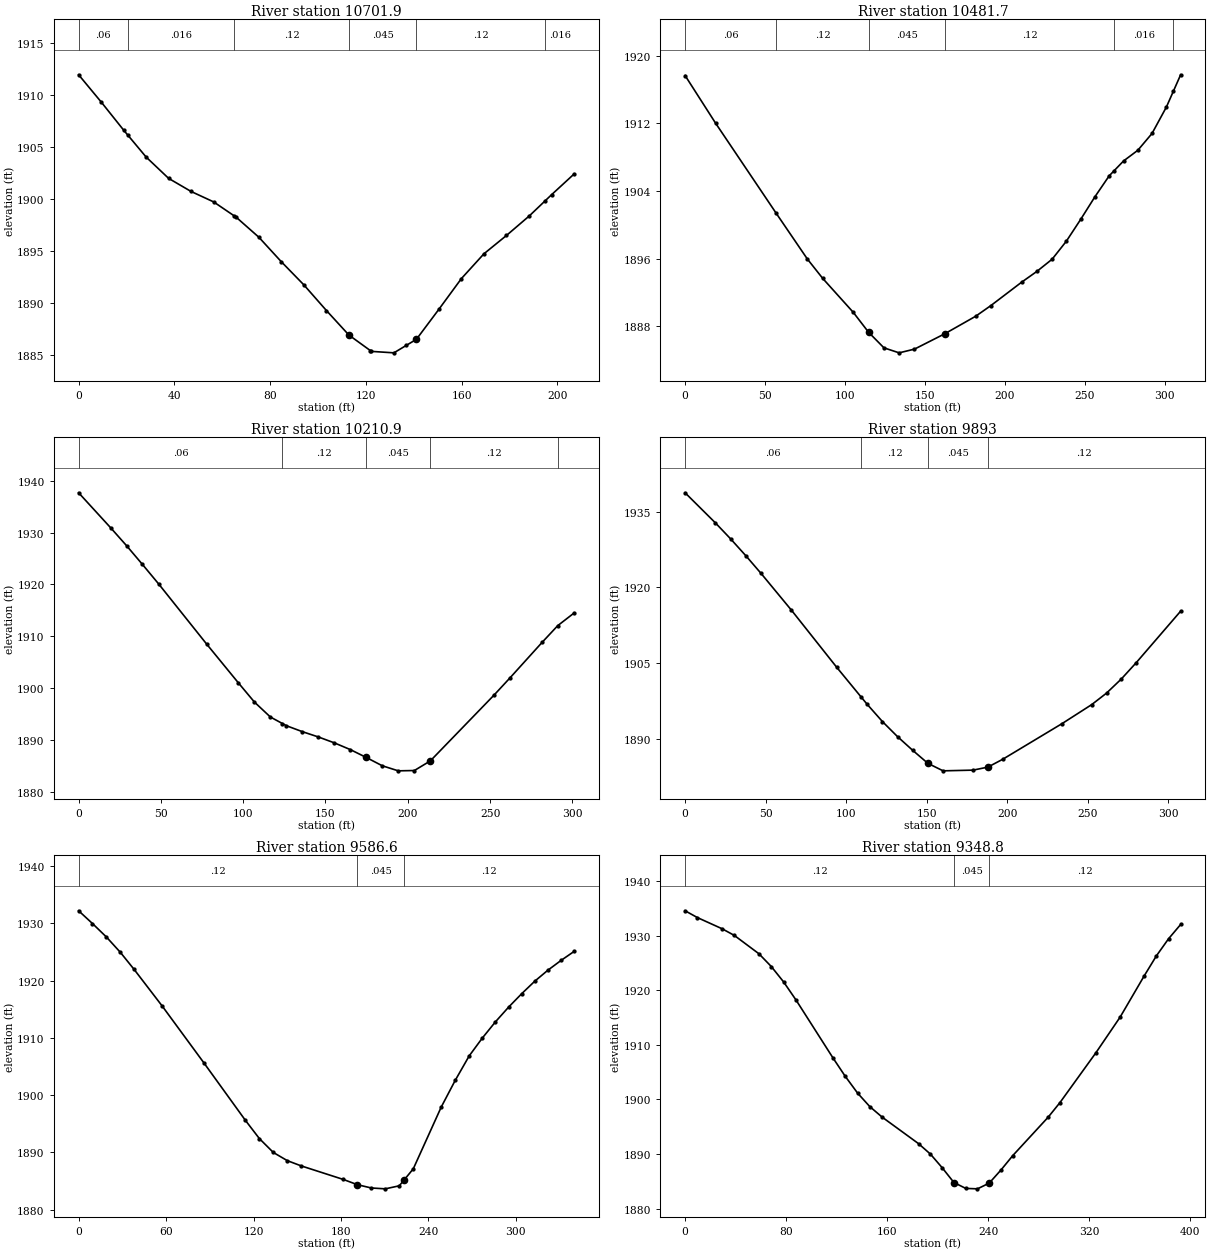
Type RM Length L Ch R = 1 ,10701.9 ,253.6,220.2,171.1
XS GIS Cut Line= 2
     1830577.289      177911.231     1830432.325      177763.515
#Sta/Elev= 28
       0 1911.95     9.4 1909.34    18.8 1906.63   20.481906.167    28.2 1904.04
    37.6 1901.99      47 1900.73    56.4 1899.73   65.061898.376    65.8 1898.26
    75.3 1896.33    84.7 1893.97    94.1 1891.75   103.5 1889.29   112.9 1886.93
   121.9 1885.43   122.3 1885.36   131.7 1885.22   136.9 1885.94   141.1 1886.52
   150.5 1889.41   159.9 1892.36   169.3 1894.74   178.7  1896.5   188.2 1898.37
  194.811899.819   197.6 1900.43     207 1902.42
#Mann= 6 ,-1 , 0
       0     .06       0   20.48    .016       0   65.06     .12       0
   112.9    .045       0   141.1     .12       0  194.81    .016       0
Bank Sta=112.9,141.1
XS Rating Curve= 0 ,0
Exp/Cntr=0.3,0.1

Type RM Length L Ch R = 1 ,10481.7 ,265.9,270.9,289.7
XS GIS Cut Line= 3
     1830743.366      177633.547     1830514.713      177654.381
     1830439.269      177626.558
#Sta/Elev= 27
       0 1917.64    19.1    1912   57.051901.338    76.5 1895.94    86.1 1893.65
   105.2 1889.64   114.8 1887.28   124.4 1885.44   133.9 1884.85   143.5 1885.29
   162.6 1887.12   181.8 1889.18   191.3 1890.44   210.5  1893.2     220 1894.47
   229.6 1895.92   238.5 1898.05   247.5 1900.64   256.4 1903.31   265.3 1905.78
  268.47  1906.4   274.3 1907.54   283.2  1908.8   292.1 1910.79   301.1 1913.92
  305.411915.765     310 1917.73
#Mann= 6 ,-1 , 0
       0     .06       0   57.05     .12       0   114.8    .045       0
   162.6     .12       0  268.47    .016       0  305.41     .12       0
Bank Sta=114.8,162.6
XS Rating Curve= 0 ,0
Exp/Cntr=0.3,0.1

Type RM Length L Ch R = 1 ,10210.9 ,317.6,317.9,316.2
XS GIS Cut Line= 2
     1830755.895      177399.487     1830454.832      177397.321
#Sta/Elev= 25
       0 1937.71    19.4 1930.97    29.1  1927.5    38.8 1923.86    48.6 1920.11
    77.7 1908.52    97.1 1900.98   106.8 1897.29   116.5  1894.4  123.861893.131
   126.3 1892.71     136 1891.56   145.7 1890.54   155.4  1889.4   165.1  1888.1
   174.8 1886.58   184.5 1884.98   194.2    1884     204 1884.06   213.7 1885.92
   252.5 1898.66   262.2 1901.99   281.6 1908.81  291.141912.052   301.1  1914.5
#Mann= 5 ,-1 , 0
       0     .06       0  123.86     .12       0   174.8    .045       0
   213.7     .12       0  291.14    .016       0
Bank Sta=174.8,213.7
XS Rating Curve= 0 ,0
Exp/Cntr=0.3,0.1

Type RM Length L Ch R = 1 ,9893    ,290.4,306.3,324.2
XS GIS Cut Line= 3
     1830766.448      177089.485     1830596.822      177088.124
     1830458.834      177093.297
#Sta/Elev= 23
       0  1938.8    18.8 1932.83    28.3 1929.64    37.7 1926.31    47.1 1922.82
      66 1915.51    94.2 1904.14  109.381898.233   113.1  1896.8   122.5  1893.4
   131.9  1890.4   141.4 1887.66   150.8 1885.09   160.2 1883.61   178.8 1883.75
     188 1884.35   197.2  1885.9   234.1 1892.99   252.5 1896.76   261.7 1899.04
   270.9 1901.85   280.1 1905.07   307.7  1915.3
#Mann= 4 ,-1 , 0
       0     .06       0  109.38     .12       0   150.8    .045       0
     188     .12       0
Bank Sta=150.8,188
XS Rating Curve= 0 ,0
Exp/Cntr=0.3,0.1

Type RM Length L Ch R = 1 ,9586.6  ,238.3,237.9,236.8
XS GIS Cut Line= 4
     1830809.188      176889.879     1830717.221      176839.557
     1830568.783      176771.848     1830496.946      176776.664
#Sta/Elev= 30
       0 1932.21     9.5 1929.98    19.1 1927.62    28.6 1924.96    38.1 1921.96
    57.2 1915.62    85.8  1905.7   114.4 1895.62     124 1892.43   133.6    1890
   143.2 1888.57   152.8 1887.65   181.6 1885.29   191.2 1884.38   200.8  1883.8
   210.4 1883.65     220 1884.18   223.2 1885.17   229.6 1887.14   248.8 1897.94
   258.4  1902.6     268 1906.88     277 1909.99     286 1912.82     295 1915.38
     304 1917.73     313 1919.92     322 1921.84     331 1923.54     340 1925.12
#Mann= 3 ,-1 , 0
       0     .12       0   191.2    .045       0   223.2     .12       0
Bank Sta=191.2,223.2
XS Rating Curve= 0 ,0
Exp/Cntr=0.3,0.1

Type RM Length L Ch R = 1 ,9348.8  ,333.5,312.3,291.2
XS GIS Cut Line= 4
     1830901.272      176748.957     1830790.137      176612.994
     1830670.346      176560.911     1830584.612      176570.391
#Sta/Elev= 30
       0 1934.53     9.8 1933.28    29.3 1931.24      39 1930.02    58.5 1926.66
    68.3 1924.32      78 1921.52    87.8 1918.22   117.1 1907.61   126.8 1904.25
   136.6 1901.17   146.3 1898.69   156.1 1896.76   184.9 1891.91   194.3    1890
   203.6 1887.51   212.9  1884.8   222.3 1883.72   231.6 1883.64   240.9 1884.69
   250.2 1887.09   259.6 1889.74   287.6 1896.76   296.9 1899.42   325.4 1908.55
   344.6 1915.08   363.7 1922.64   373.3 1926.28   382.9  1929.4   392.5 1932.02
#Mann= 3 ,-1 , 0
       0     .12       0   212.9    .045       0   240.9     .12       0
Bank Sta=212.9,240.9
XS Rating Curve= 0 ,0
Exp/Cntr=0.3,0.1