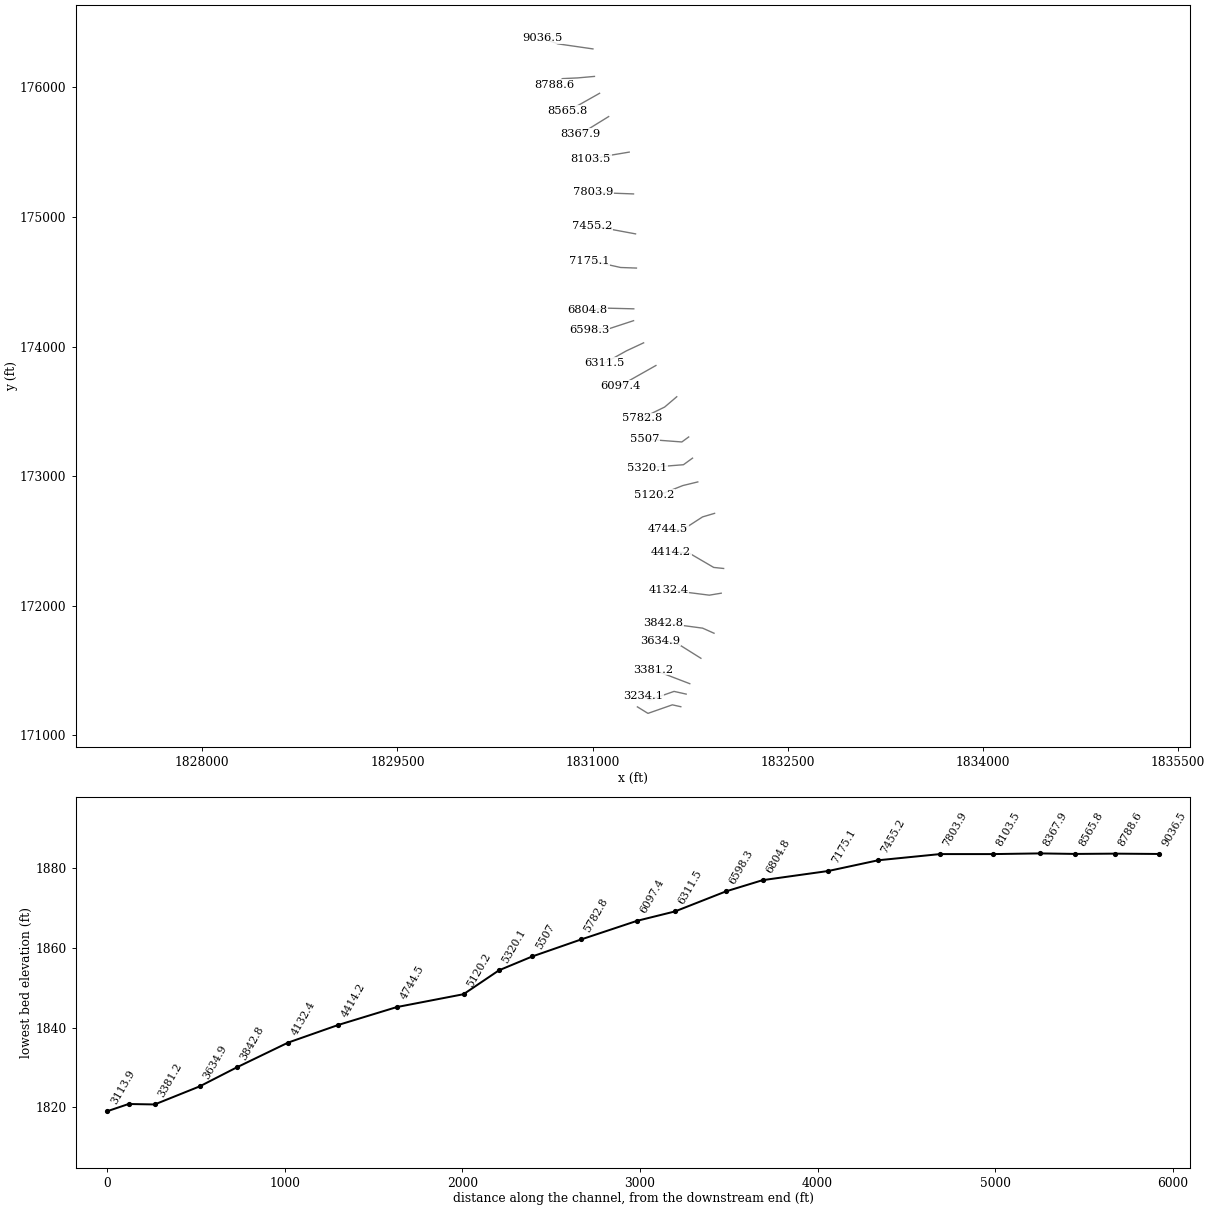
HEC-RAS study ZEBSCK.prj: ZEBSCK

--- ZEBSCK.g01 (geometry) --- (continued)

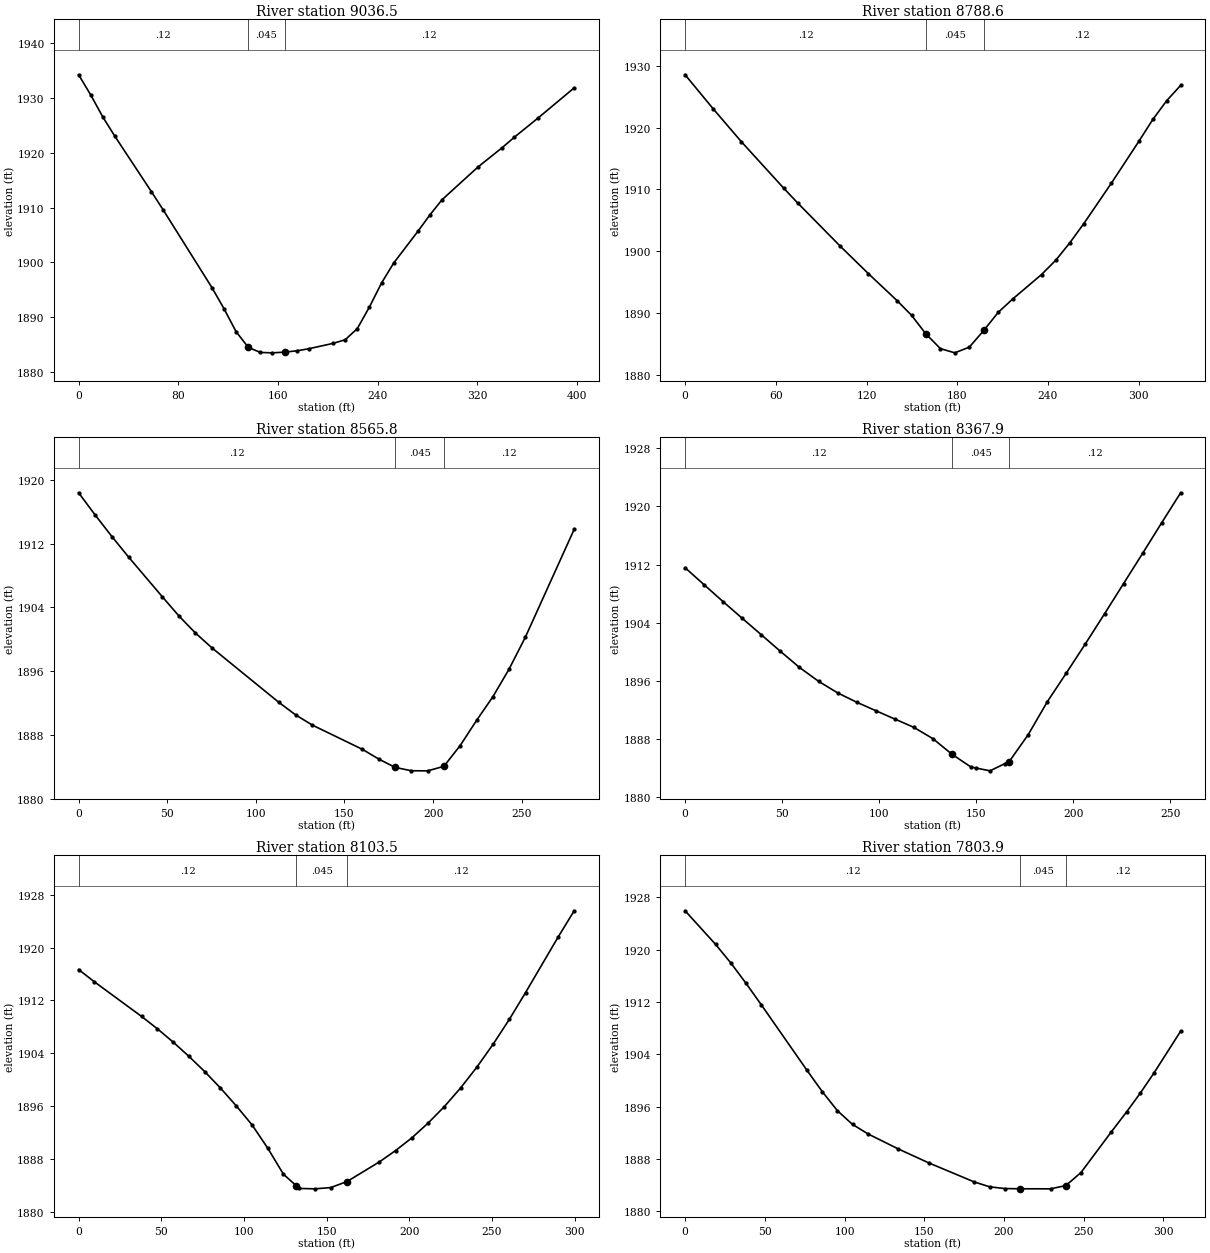
Type RM Length L Ch R = 1 ,9036.5  ,240.6,247.9,254.9
XS GIS Cut Line= 3
     1831002.383       176297.88     1830732.846      176336.953
     1830614.819      176379.557
#Sta/Elev= 30
       0 1934.27     9.7 1930.59    19.4 1926.57    29.2    1923    58.4 1912.93
    68.1 1909.51     107  1895.4   116.7 1891.54   126.4 1887.35   135.8  1884.6
   136.2 1884.48   145.9 1883.55   155.6 1883.48   165.4 1883.61   175.1 1883.85
   184.8 1884.23   204.3 1885.21     214 1885.87   223.7 1887.91   233.4 1891.83
   243.2 1896.25   252.9 1899.88   272.4 1905.69     282 1908.68   291.7 1911.44
   320.6 1917.43   339.9 1920.94   349.6 1922.83   368.9 1926.39   397.8 1931.88
#Mann= 3 ,-1 , 0
       0     .12       0   135.8    .045       0   165.4     .12       0
Bank Sta=135.8,165.4
XS Rating Curve= 0 ,0
Exp/Cntr=0.3,0.1

Type RM Length L Ch R = 1 ,8788.6  ,205.9,222.8,239.9
XS GIS Cut Line= 4
     1831014.004      176085.584     1830883.887      176073.932
     1830769.304      176068.723     1830702.115      176020.969
#Sta/Elev= 25
       0 1928.54    18.7    1923    37.3 1917.69    65.3 1910.18    74.6 1907.77
   102.6 1900.82   121.3 1896.36   140.2 1892.01   149.8 1889.63   159.3 1886.62
   168.9 1884.24   178.4 1883.56     188 1884.48   197.6 1887.19   207.1  1890.1
   216.7 1892.27   235.8 1896.23   245.3 1898.57   254.5 1901.36   263.7 1904.45
     282 1911.01   300.3 1917.83   309.4 1921.31   318.6 1924.36   327.8 1926.82
#Mann= 3 ,-1 , 0
       0     .12       0   159.3    .045       0   197.6     .12       0
Bank Sta=159.3,197.6
XS Rating Curve= 0 ,0
Exp/Cntr=0.3,0.1

Type RM Length L Ch R = 1 ,8565.8  ,195.8,197.9,200.1
XS GIS Cut Line= 3
     1831053.283       175955.18     1830905.906      175871.597
     1830809.016      175819.241
#Sta/Elev= 23
       0 1918.39     9.4 1915.58    18.8 1912.89    28.2 1910.32    47.1 1905.37
    56.5 1902.95    65.9 1900.79    75.3 1898.91     113 1892.08   122.4 1890.52
   131.8 1889.24     160  1886.2   169.4 1884.96   178.6 1883.92   187.8  1883.5
     197 1883.49   206.1 1884.06   215.3 1886.67   224.5 1889.81   233.7 1892.78
   242.8 1896.23     252 1900.24   279.6  1913.8
#Mann= 3 ,-1 , 0
       0     .12       0   178.6    .045       0   206.1     .12       0
Bank Sta=178.6,206.1
XS Rating Curve= 0 ,0
Exp/Cntr=0.3,0.1

Type RM Length L Ch R = 1 ,8367.9  ,279.5,264.4,249.8
XS GIS Cut Line= 2
     1831123.165       175775.51     1830906.151      175640.962
#Sta/Elev= 29
       0 1911.56     9.8 1909.22    19.6 1906.89    29.5 1904.59    39.3 1902.33
    49.1 1900.06    58.9 1897.85    68.8 1895.93    78.6 1894.34    88.4 1893.06
    98.2  1891.9     108 1890.75   117.8 1889.61   127.7 1888.04   137.5  1885.9
   147.3 1884.14   149.8 1884.01   157.1 1883.62   164.8 1884.62     167  1884.9
   176.8 1888.61   186.6 1893.12   196.4 1897.07   206.2 1901.08   216.1 1905.22
   225.9 1909.38   235.7 1913.53   245.5 1917.73   255.3 1921.87
#Mann= 3 ,-1 , 0
       0     .12       0   137.5    .045       0     167     .12       0
Bank Sta=137.5,167
XS Rating Curve= 0 ,0
Exp/Cntr=0.3,0.1

Type RM Length L Ch R = 1 ,8103.5  ,307.1,299.6,291.6
XS GIS Cut Line= 3
     1831281.094      175501.226       1831130.7       175475.77
     1830986.648       175445.03
#Sta/Elev= 29
       0 1916.69     9.5 1914.84    38.1 1909.58    47.7  1907.7    57.2 1905.69
    66.7 1903.54    76.3 1901.22    85.8 1898.73    95.3 1896.05   104.9 1893.15
   114.4 1889.62   123.9 1885.67   131.8 1883.89   133.5 1883.51     143 1883.45
   152.5 1883.64   162.4 1884.56     182 1887.54   191.8 1889.26   201.6 1891.18
   211.4 1893.41   221.3 1895.93   231.1 1898.75   240.9 1901.89   250.7 1905.35
   260.6 1909.15   270.4 1913.21     290 1921.58   299.8  1925.6
#Mann= 3 ,-1 , 0
       0     .12       0   131.8    .045       0   162.4     .12       0
Bank Sta=131.8,162.4
XS Rating Curve= 0 ,0
Exp/Cntr=0.3,0.1

Type RM Length L Ch R = 1 ,7803.9  ,354.4,348.7,342.6
XS GIS Cut Line= 3
     1831314.296       175178.34     1831037.533      175188.515
     1831003.752      175190.518
#Sta/Elev= 24
       0 1925.95    19.1 1920.82    28.6    1918    38.2 1914.87    47.8 1911.58
    76.4 1901.58      86 1898.32    95.5  1895.4     105  1893.3   114.6 1891.86
   133.7 1889.55   152.8 1887.42   181.4  1884.5     191 1883.76   200.6 1883.49
   210.1 1883.46   229.2 1883.45   238.8 1883.95   248.3 1885.94   267.4 1892.18
     277 1895.24   285.4 1898.05   293.9 1901.09   310.8 1907.54
#Mann= 3 ,-1 , 0
       0     .12       0   210.1    .045       0   238.8     .12       0
Bank Sta=210.1,238.8
XS Rating Curve= 0 ,0
Exp/Cntr=0.3,0.1

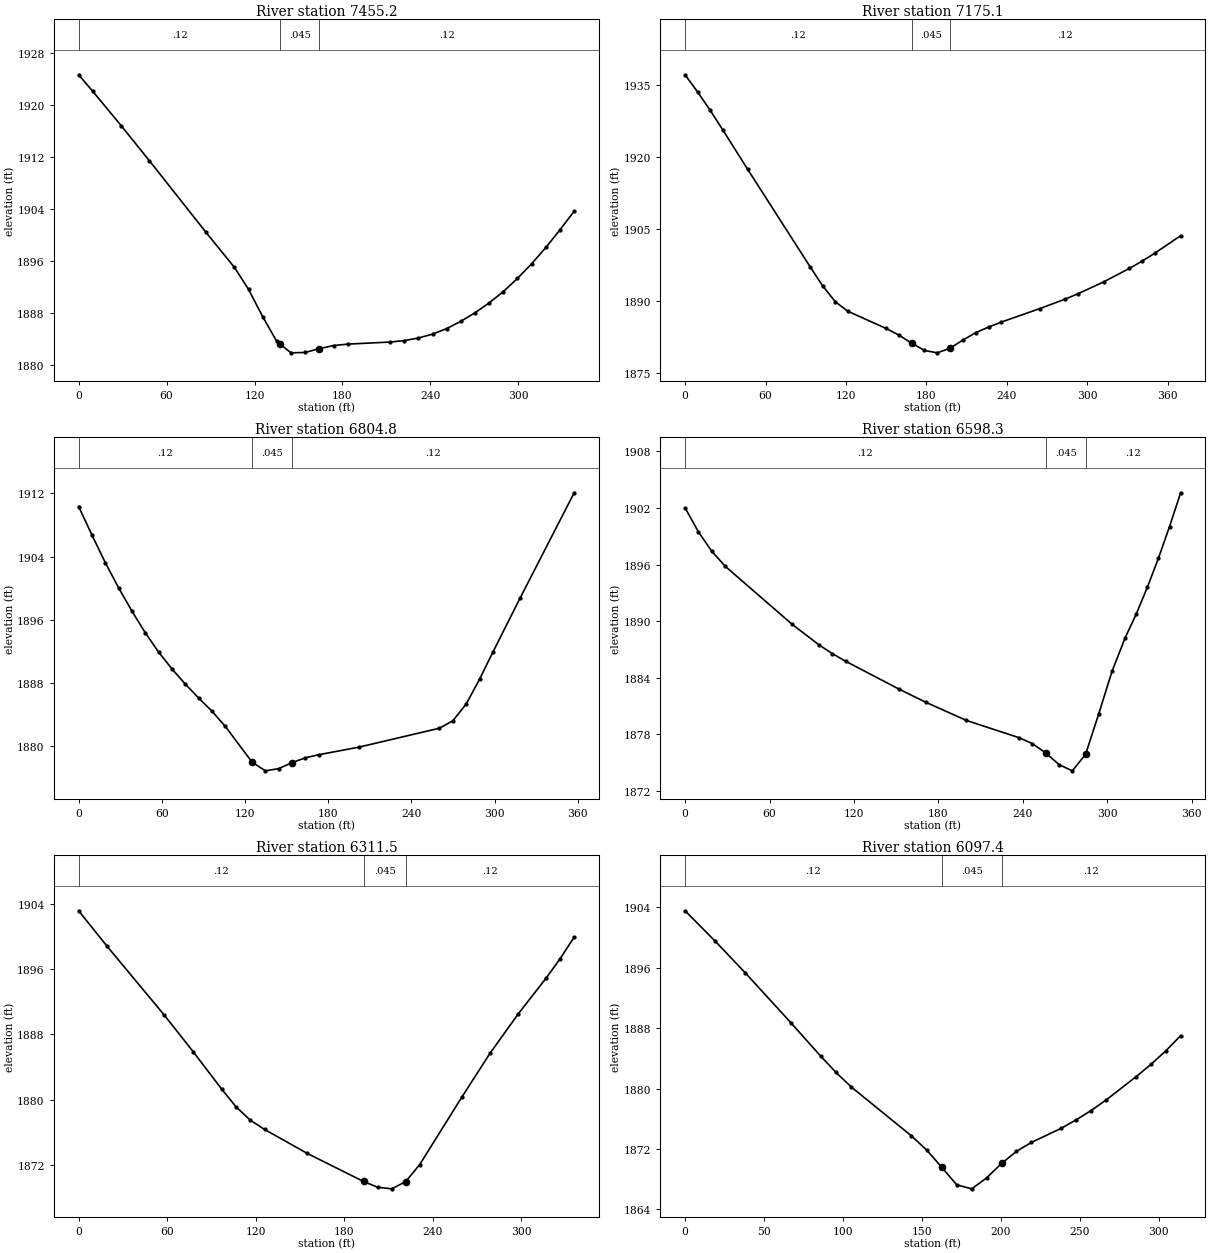
Type RM Length L Ch R = 1 ,7455.2  ,280.9,280,278.4
XS GIS Cut Line= 2
     1831329.827      174869.821     1830997.466      174931.772
#Sta/Elev= 29
       0 1924.66     9.7  1922.1      29 1916.84    48.3 1911.44    86.9 1900.43
   106.3 1895.04   115.9 1891.67   125.6 1887.45   135.2 1883.65   137.7  1883.2
   144.9  1881.9   154.6 1881.96   164.2 1882.54   173.9 1883.02   183.5 1883.24
   212.5 1883.56   222.2 1883.78   231.8 1884.18   241.5 1884.78   251.2 1885.64
   260.8 1886.75   270.5 1888.07   280.1 1889.58   289.8 1891.33   299.4 1893.34
   309.1  1895.6   318.8  1898.1   328.4 1900.82   338.1 1903.68
#Mann= 3 ,-1 , 0
       0     .12       0   137.7    .045       0   164.2     .12       0
Bank Sta=137.7,164.2
XS Rating Curve= 0 ,0
Exp/Cntr=0.3,0.1

Type RM Length L Ch R = 1 ,7175.1  ,361.2,370.4,381.5
XS GIS Cut Line= 3
       1831336.7      174605.954     1831215.558      174610.307
     1830973.201      174664.164
#Sta/Elev= 27
       0 1937.09     9.3 1933.53    18.6 1929.73      28 1925.67    46.6 1917.44
    93.2 1897.14   102.6 1893.15   111.9 1889.89   121.2 1887.89   149.9  1884.3
   159.4 1882.91     169 1881.23   178.5 1879.71   188.1 1879.22   197.6  1880.2
   207.2 1881.89   216.7 1883.42   226.3 1884.58   235.8 1885.62   264.4 1888.42
   283.6 1890.42   293.1 1891.54   312.2    1894   331.3 1896.79   340.8 1898.31
   350.4 1899.98   369.5  1903.6
#Mann= 3 ,-1 , 0
       0     .12       0     169    .045       0   197.6     .12       0
Bank Sta=169,197.6
XS Rating Curve= 0 ,0
Exp/Cntr=0.3,0.1

Type RM Length L Ch R = 1 ,6804.8  ,205.2,206.4,202.5
XS GIS Cut Line= 3
     1831316.418      174291.175     1831095.203      174296.799
     1830960.138      174280.112
#Sta/Elev= 26
       0 1910.34     9.6 1906.74    19.2 1903.26    28.9 1900.04    38.5  1897.1
    48.1 1894.37    57.7 1891.93    67.4 1889.79      77 1887.88    86.6 1886.12
    96.2 1884.46   105.8 1882.54   125.1 1878.02   134.7 1876.92   144.3  1877.2
   153.9 1877.96   163.6 1878.57   173.2 1878.96     202 1879.91   260.2 1882.31
   269.9 1883.25   279.6 1885.39   289.3 1888.55     299 1892.01   318.5  1898.8
   357.4 1912.08
#Mann= 3 ,-1 , 0
       0     .12       0   125.1    .045       0   153.9     .12       0
Bank Sta=125.1,153.9
XS Rating Curve= 0 ,0
Exp/Cntr=0.3,0.1

Type RM Length L Ch R = 1 ,6598.3  ,269.4,286.9,306.3
XS GIS Cut Line= 4
      1831314.55      174199.712     1831124.717      174137.077
     1831011.842      174138.863      1830973.58      174129.539
#Sta/Elev= 25
       0 1902.01     9.5 1899.45      19  1897.4    28.6  1895.8    76.2 1889.64
    95.2 1887.47   104.7 1886.54   114.2 1885.73   152.3 1882.76   171.3 1881.37
   199.9 1879.46   237.5 1877.62   246.9 1876.99   256.3 1876.01   265.8 1874.77
   275.2 1874.11   284.6 1875.85     294 1880.16   303.4 1884.65   312.8 1888.24
   320.7 1890.76   328.5 1893.57   336.4 1896.66   344.3 1900.02   352.2 1903.61
#Mann= 3 ,-1 , 0
       0     .12       0   256.3    .045       0   284.6     .12       0
Bank Sta=256.3,284.6
XS Rating Curve= 0 ,0
Exp/Cntr=0.3,0.1

Type RM Length L Ch R = 1 ,6311.5  ,213.6,214.1,214.7
XS GIS Cut Line= 3
     1831391.933      174028.687     1831260.134      173966.938
      1831094.01      173873.734
#Sta/Elev= 20
       0 1903.14    19.4 1898.77    58.2 1890.34    77.6  1885.9      97  1881.3
   106.7 1879.14   116.4  1877.5   126.1 1876.36   155.1 1873.42   193.2 1869.99
   202.7 1869.29   212.2 1869.09   221.7 1869.96   231.3 1872.07   259.8 1880.31
   278.9 1885.68   297.9 1890.47     317  1894.9   326.5 1897.28     336 1899.91
#Mann= 3 ,-1 , 0
       0     .12       0   193.2    .045       0   221.7     .12       0
Bank Sta=193.2,221.7
XS Rating Curve= 0 ,0
Exp/Cntr=0.3,0.1

Type RM Length L Ch R = 1 ,6097.4  ,317.7,314.6,311.4
XS GIS Cut Line= 3
     1831486.484      173853.721      1831336.87      173768.858
     1831213.644      173698.641
#Sta/Elev= 24
       0 1903.51    19.1 1899.48    38.2 1895.28    66.9 1888.72      86 1884.25
    95.6 1882.12   105.1 1880.23   143.3 1873.74   152.9 1871.88   162.4 1869.61
     172 1867.26   181.5 1866.73   190.9 1868.17   200.4 1870.09   209.8 1871.68
   219.3 1872.87   238.2 1874.74   247.6 1875.85   257.1 1877.09   266.6 1878.48
   285.5 1881.55   294.9 1883.18   304.4 1884.98   313.8 1886.99
#Mann= 3 ,-1 , 0
       0     .12       0   162.4    .045       0   200.4     .12       0
Bank Sta=162.4,200.4
XS Rating Curve= 0 ,0
Exp/Cntr=0.3,0.1

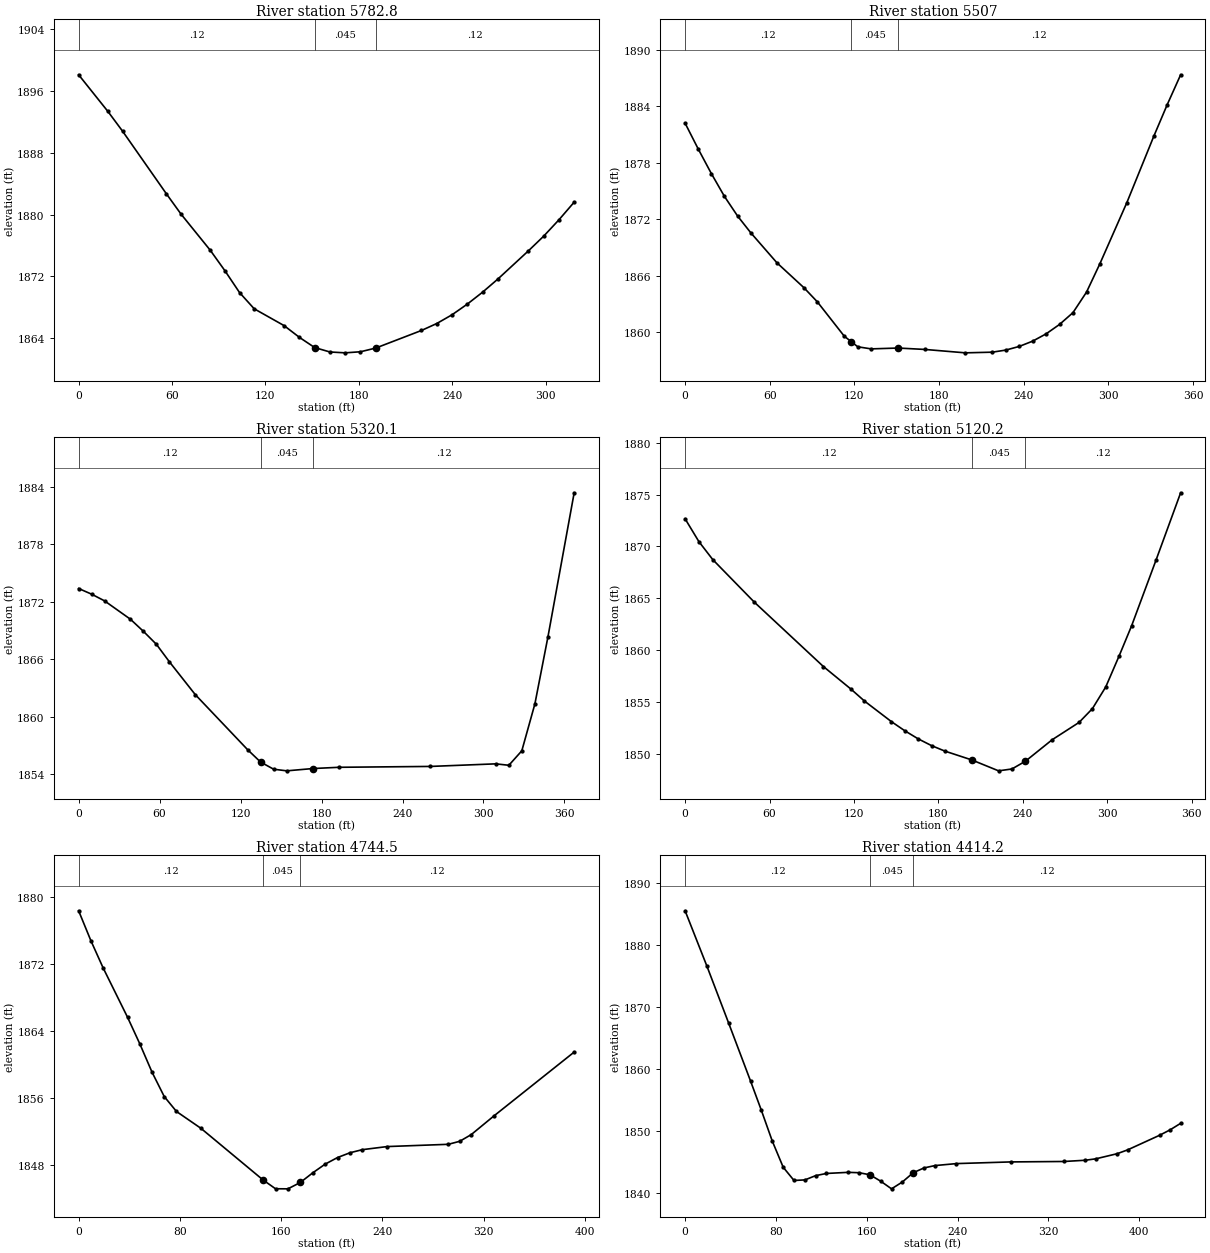
Type RM Length L Ch R = 1 ,5782.8  ,295.3,275.8,256.4
XS GIS Cut Line= 3
     1831646.467      173612.324     1831553.536       173532.91
     1831377.371      173446.638
#Sta/Elev= 26
       0 1898.11    18.8 1893.36    28.2 1890.81    56.4 1882.68    65.8 1880.05
    84.6 1875.36      94 1872.71   103.4 1869.88   112.8 1867.78     132  1865.6
   141.9 1864.07   151.7 1862.75   161.5 1862.18   171.3 1862.07   181.1 1862.21
   190.9 1862.69   220.3 1864.97   230.1 1865.87   239.9    1867   249.7 1868.38
   259.6 1869.94   269.4 1871.64     289 1875.29   298.8 1877.19   308.6 1879.31
   318.4  1881.6
#Mann= 3 ,-1 , 0
       0     .12       0   151.7    .045       0   190.9     .12       0
Bank Sta=151.7,190.9
XS Rating Curve= 0 ,0
Exp/Cntr=0.3,0.1

Type RM Length L Ch R = 1 ,5507    ,180.8,186.9,193
XS GIS Cut Line= 3
     1831738.218      173301.894     1831685.698      173263.379
     1831400.422      173284.941
#Sta/Elev= 29
       0 1882.19     9.3 1879.45    18.6 1876.84    27.9 1874.41    37.2 1872.33
    46.5 1870.56    65.1 1867.36    84.2 1864.72    93.7 1863.22   112.8 1859.57
   117.8 1858.98   122.4 1858.44   131.9 1858.22     151 1858.31     170 1858.16
   198.6  1857.8   217.7 1857.87   227.2 1858.09   236.8 1858.48   246.3 1859.04
   255.9 1859.82   265.4 1860.82   274.9 1862.07   284.5 1864.25     294 1867.27
   313.1 1873.76   332.2 1880.81   341.7 1884.16   351.2 1887.33
#Mann= 3 ,-1 , 0
       0     .12       0   117.8    .045       0     151     .12       0
Bank Sta=117.8,151
XS Rating Curve= 0 ,0
Exp/Cntr=0.3,0.1

Type RM Length L Ch R = 1 ,5320.1  ,185.4,199.8,215.4
XS GIS Cut Line= 3
     1831767.794      173138.411     1831697.851      173087.598
     1831418.042      173065.213
#Sta/Elev= 21
       0 1873.37     9.6 1872.78    19.2 1872.08    38.4 1870.16      48  1868.9
    57.6 1867.55    67.2 1865.73    86.4  1862.3   125.2 1856.55   134.8 1855.26
   144.5 1854.51   154.2 1854.34   173.6 1854.58   192.9 1854.71   260.7  1854.8
   309.1 1855.07   318.8 1854.92   328.4 1856.43   338.1 1861.33   347.8 1868.35
   367.2 1883.36
#Mann= 3 ,-1 , 0
       0     .12       0   134.8    .045       0   173.6     .12       0
Bank Sta=134.8,173.6
XS Rating Curve= 0 ,0
Exp/Cntr=0.3,0.1

Type RM Length L Ch R = 1 ,5120.2  ,372.3,375.7,360.8
XS GIS Cut Line= 4
      1831808.26       172954.82     1831693.608      172926.856
     1831516.525      172856.543     1831472.841      172856.543
#Sta/Elev= 24
       0 1872.66     9.8 1870.46    19.7 1868.72    49.2 1864.62    98.3 1858.41
     118 1856.22   127.5 1855.08   146.6  1853.1   156.1 1852.22   165.6 1851.44
   175.2 1850.78   184.7 1850.25   203.8  1849.4   222.8 1848.35   232.3 1848.53
   241.9 1849.28   260.9 1851.35     280 1853.02   289.5 1854.35     299 1856.45
   308.5 1859.44   317.3 1862.32   334.8 1868.71   352.2 1875.17
#Mann= 3 ,-1 , 0
       0     .12       0   203.8    .045       0   241.9     .12       0
Bank Sta=203.8,241.9
XS Rating Curve= 0 ,0
Exp/Cntr=0.3,0.1

Type RM Length L Ch R = 1 ,4744.5  ,372.6,330.4,304.8
XS GIS Cut Line= 4
     1831937.252      172712.192      1831844.65      172684.668
       1831688.4      172583.106     1831580.071       172587.92
#Sta/Elev= 24
       0 1878.35     9.7 1874.77    19.3 1871.54    38.6 1865.64    48.3 1862.46
      58 1859.06    67.6 1856.16    77.3 1854.37    96.6 1852.36   145.6  1846.2
   155.5 1845.14   165.3 1845.13   175.1 1845.89   184.9 1847.04   194.7 1848.08
   204.5 1848.87   214.3 1849.44   224.1 1849.81   243.7 1850.18     292 1850.45
     301 1850.81   310.1 1851.61   328.1 1853.85   391.4 1861.47
#Mann= 3 ,-1 , 0
       0     .12       0   145.6    .045       0   175.1     .12       0
Bank Sta=145.6,175.1
XS Rating Curve= 0 ,0
Exp/Cntr=0.3,0.1

Type RM Length L Ch R = 1 ,4414.2  ,266.5,281.8,296.9
XS GIS Cut Line= 4
     1832006.905      172286.608      1831930.49      172294.629
     1831741.253       172405.74     1831601.491       172416.44
#Sta/Elev= 30
       0 1885.47    19.2 1876.55    38.4 1867.34    57.6 1858.04    67.2 1853.28
    76.8 1848.33    86.4 1844.12    95.9 1841.99   105.5 1842.08     115 1842.77
   124.5 1843.12   143.6  1843.3   153.2 1843.24   162.7 1842.91   172.2 1841.88
   181.8 1840.64   191.3 1841.74   200.9 1843.24   210.4 1844.01     220 1844.39
     239 1844.71   286.7 1844.98   333.7 1845.05   352.4 1845.25   361.7 1845.48
   380.4  1846.3   389.7 1846.92   417.8 1849.27   427.1 1850.15   436.4  1851.2
#Mann= 3 ,-1 , 0
       0     .12       0   162.7    .045       0   200.9     .12       0
Bank Sta=162.7,200.9
XS Rating Curve= 0 ,0
Exp/Cntr=0.3,0.1

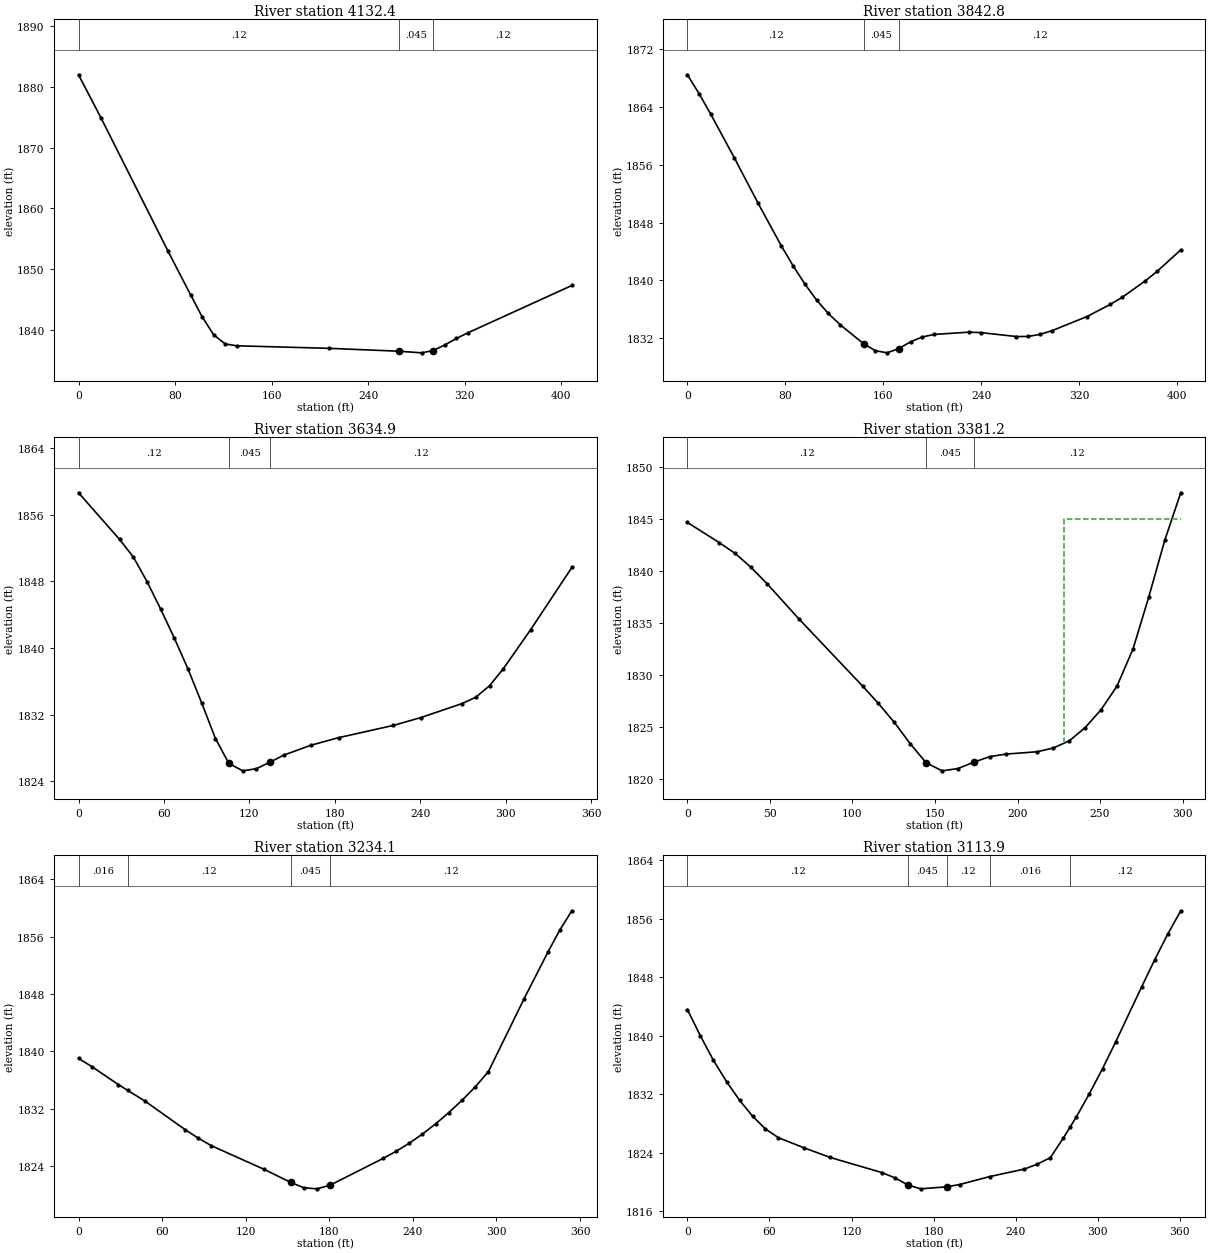
Type RM Length L Ch R = 1 ,4132.4  ,291.7,289.6,287.4
XS GIS Cut Line= 3
     1831988.315      172095.765     1831896.733      172080.501
     1831583.285      172120.422
#Sta/Elev= 16
       0 1881.98    18.6  1874.9    74.3 1852.91    92.8  1845.8   102.4 1842.18
     112 1839.19   121.6 1837.69   131.2 1837.39   207.8 1836.97   265.2  1836.5
   284.4 1836.23   293.9 1836.61   303.5 1837.53   313.1 1838.59   322.6 1839.52
   408.8 1847.31
#Mann= 3 ,-1 , 0
       0     .12       0   265.2    .045       0   293.9     .12       0
Bank Sta=265.2,293.9
XS Rating Curve= 0 ,0
Exp/Cntr=0.3,0.1

Type RM Length L Ch R = 1 ,3842.8  ,222.6,207.9,194.2
XS GIS Cut Line= 3
     1831932.975       171786.71      1831845.42      171825.879
      1831541.02      171866.713
#Sta/Elev= 30
       0 1868.39     9.6 1865.76    19.2 1862.91    38.4  1856.9    57.6  1850.7
    76.7 1844.78    86.3 1842.03    95.9 1839.52   105.5  1837.3   115.1 1835.44
   124.7  1833.9   143.9 1831.27   153.5 1830.31   163.1 1830.01   172.7  1830.6
   182.3 1831.53   191.9  1832.2   201.5 1832.55   230.3 1832.87   239.9  1832.8
   268.7 1832.26   278.3 1832.27   287.9 1832.55   297.5 1833.05   326.3 1835.01
   345.5  1836.7   355.1 1837.67   374.2 1839.96   383.8 1841.27     403 1844.22
#Mann= 3 ,-1 , 0
       0     .12       0   143.9    .045       0   172.7     .12       0
Bank Sta=143.9,172.7
XS Rating Curve= 0 ,0
Exp/Cntr=0.3,0.1

Type RM Length L Ch R = 1 ,3634.9  ,246.5,253.7,259.8
XS GIS Cut Line= 3
     1831832.196      171593.213     1831661.392      171700.879
     1831519.547      171729.125
#Sta/Elev= 24
       0 1858.62    28.8 1853.03    38.5 1850.92    48.1 1847.97    57.7 1844.67
    67.3 1841.19    76.9 1837.49    86.5 1833.42    96.2 1829.14   105.6 1826.16
   115.4 1825.27     125 1825.53   134.6 1826.32   144.2 1827.16   163.4 1828.35
   182.7 1829.25   221.2 1830.72   240.5 1831.66   269.4 1833.34     279 1834.09
   288.7 1835.48   298.3  1837.5   317.6 1842.21   346.5 1849.66
#Mann= 3 ,-1 , 0
       0     .12       0   105.6    .045       0   134.6     .12       0
Bank Sta=105.6,134.6
XS Rating Curve= 0 ,0
Exp/Cntr=0.3,0.1

Type RM Length L Ch R = 1 ,3381.2  ,115.8,147.1,178.2
XS GIS Cut Line= 2
     1831746.607      171397.087     1831467.681      171504.494
#Sta/Elev= 26
       0 1844.66    19.3 1842.72    28.9 1841.68    38.6 1840.33    48.2 1838.77
    67.5 1835.38   106.1 1828.91   115.7 1827.23   125.3 1825.42     135 1823.35
   144.6 1821.52   154.3 1820.74   163.9 1820.96   173.6 1821.58   183.2 1822.11
   192.8 1822.35   212.1 1822.58   221.8 1822.95   231.4 1823.63     241 1824.91
   250.7 1826.64   260.3 1828.91     270 1832.49   279.6 1837.52   289.2 1842.94
   298.9 1847.52
#Mann= 3 ,-1 , 0
       0     .12       0   144.6    .045       0   173.6     .12       0
#XS Ineff= 2 , 0
                          228.26         1844.97
Permanent Ineff=
       F       F
Bank Sta=144.6,173.6
XS Rating Curve= 0 ,0
Exp/Cntr=0.3,0.1

Type RM Length L Ch R = 1 ,3234.1  ,119.9,120.2,125.2
XS GIS Cut Line= 4
     1831718.925      171316.679     1831625.802      171337.598
     1831438.302      171271.626     1831387.385      171303.146
#Sta/Elev= 26
       0 1839.03     9.5  1837.9    28.6 1835.38   35.271834.574    47.7 1833.08
    76.4 1829.12    85.9 1827.92    95.4 1826.86   133.3 1823.56   152.2 1821.76
   161.7    1821   171.2 1820.85   180.6 1821.36   218.5 1825.08     228 1826.09
   237.4 1827.21   246.9 1828.49   256.4 1829.92   265.8 1831.48   275.3  1833.2
   284.8 1835.07   294.2 1837.19   319.9 1847.38     337 1853.88   345.5 1856.94
   354.1 1859.61
#Mann= 4 ,-1 , 0
       0    .016       0   35.27     .12       0   152.2    .045       0
   180.6     .12       0
Bank Sta=152.2,180.6
XS Rating Curve= 0 ,0
Exp/Cntr=0.3,0.1

Type RM Length L Ch R = 1 ,3113.9  ,167.2,132.8,94.1
XS GIS Cut Line= 4
     1831677.784      171219.263     1831612.781      171233.865
     1831425.281      171167.893     1831344.168      171218.106
#Sta/Elev= 30
       0 1843.56     9.5 1839.97      19 1836.63    28.6 1833.71    38.1 1831.17
    47.6 1828.99    57.1 1827.23    66.6 1826.03    85.6 1824.63   104.5 1823.33
   142.3 1821.26   151.8 1820.54   161.3 1819.56   170.7 1819.04   189.7 1819.32
   199.1 1819.63  221.311820.727   246.5 1821.75   255.9 1822.42   265.4  1823.3
   274.9 1825.98  279.851827.486   284.5  1828.9     294 1832.07   303.6 1835.48
   313.1  1839.1   332.2 1846.67   341.7 1850.36   351.2 1853.86   360.8 1857.08
#Mann= 5 ,-1 , 0
       0     .12       0   161.3    .045       0   189.7     .12       0
  221.31    .016       0  279.85     .12       0
Bank Sta=161.3,189.7
XS Rating Curve= 0 ,0
Exp/Cntr=0.3,0.1