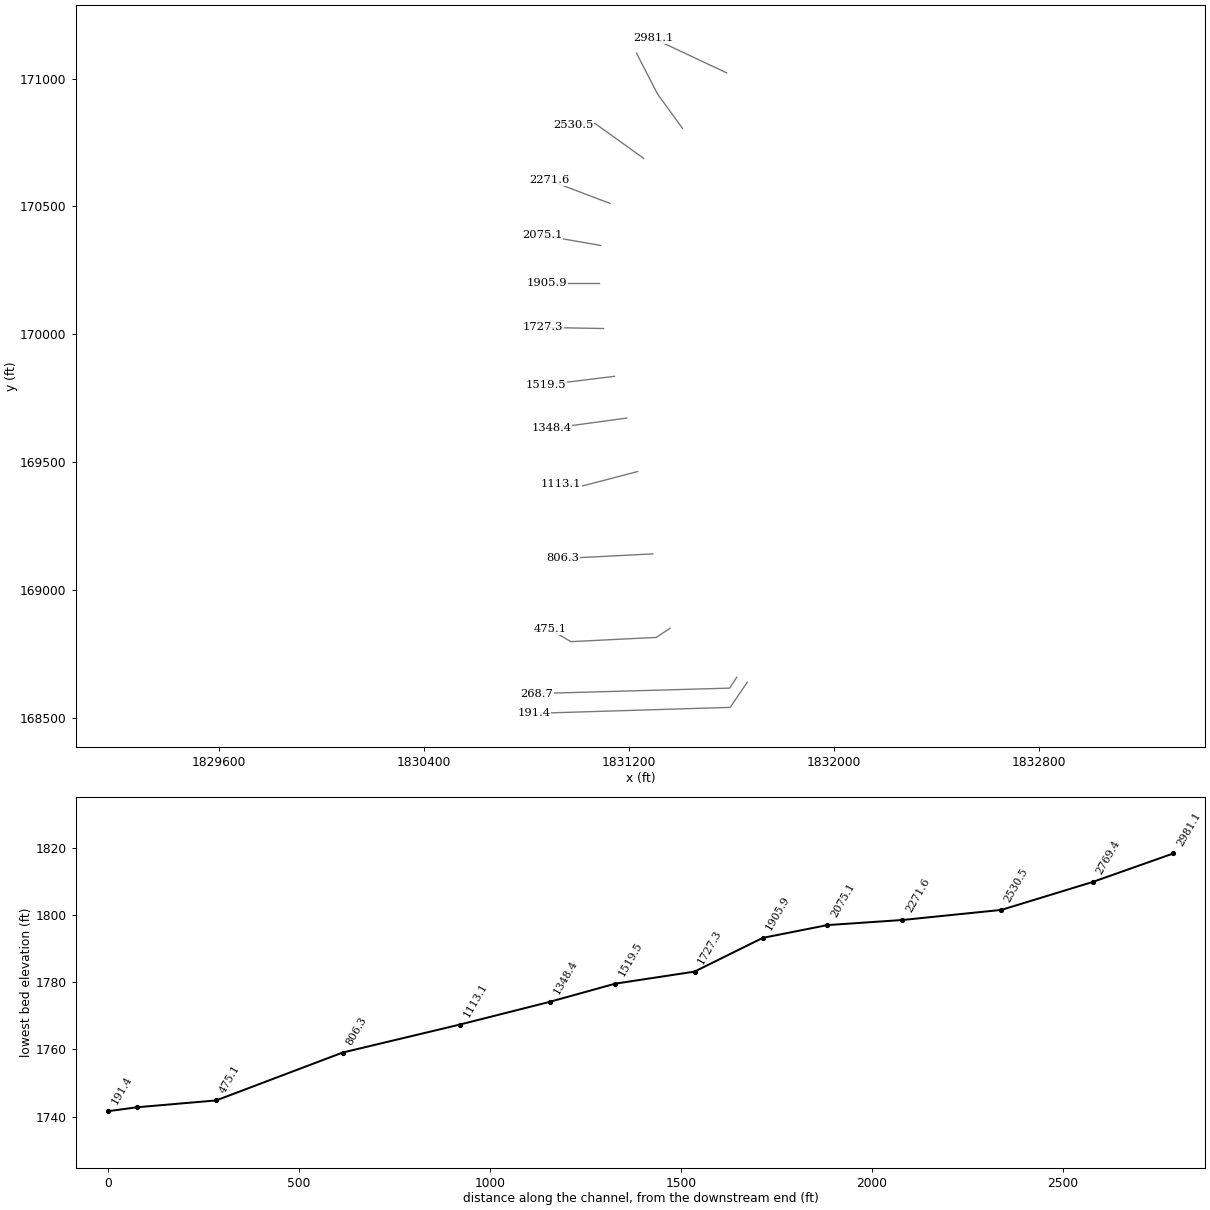
HEC-RAS study ZEBSCK.prj: ZEBSCK

--- ZEBSCK.g01 (geometry) --- (continued)

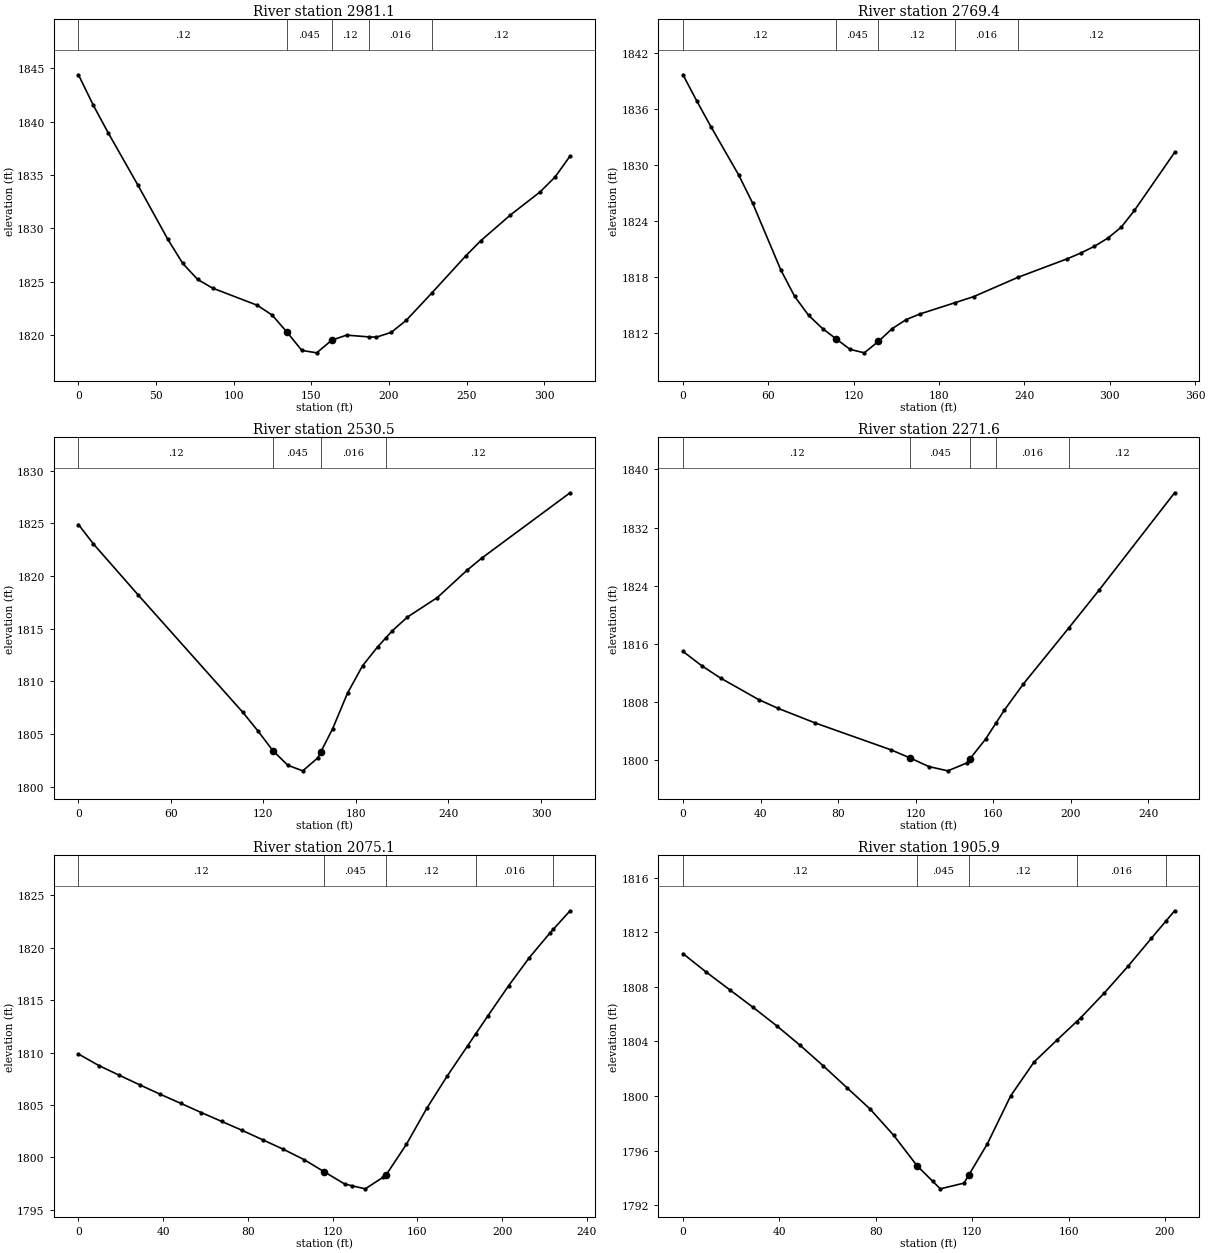
Type RM Length L Ch R = 1 ,2981.1  ,230.7,211.7,192.5
XS GIS Cut Line= 2
     1831582.391      171022.386     1831295.914      171157.338
#Sta/Elev= 26
       0 1844.41     9.6 1841.55    19.2 1838.96    38.4 1834.04    57.6 1828.98
    67.2 1826.72    76.8 1825.22    86.4 1824.41   115.2  1822.8   124.8 1821.88
   134.4 1820.27   143.9 1818.57   153.5 1818.34   163.1 1819.52   172.7    1820
  187.171819.835   191.9 1819.81   201.5 1820.26   211.1 1821.38  227.571823.938
   249.5 1827.43   259.1 1828.84   278.3 1831.27   297.5 1833.44   307.1 1834.84
   316.7 1836.79
#Mann= 5 ,-1 , 0
       0     .12       0   134.4    .045       0   163.1     .12       0
  187.17    .016       0  227.57     .12       0
Bank Sta=134.4,163.1
XS Rating Curve= 0 ,0
Exp/Cntr=0.3,0.1

Type RM Length L Ch R = 1 ,2769.4  ,226.1,238.8,251.4
XS GIS Cut Line= 3
     1831410.156      170805.357     1831312.434      170940.462
     1831230.698      171099.575
#Sta/Elev= 26
       0 1839.69     9.8 1836.85    19.6 1834.13    39.2 1828.92      49  1825.9
    68.7 1818.76    78.5 1815.89    88.3 1813.86    98.1 1812.44   107.9  1811.3
   117.5  1810.2   127.5 1809.83   137.3 1811.05   147.1 1812.43   156.9  1813.4
   166.7 1814.01  190.971815.201   204.4 1815.87  235.66 1817.95   270.3 1819.94
   279.7 1820.55   289.1 1821.26   298.6 1822.14     308 1823.31   317.4 1825.13
   345.6 1831.35
#Mann= 5 ,-1 , 0
       0     .12       0   107.9    .045       0   137.3     .12       0
  190.97    .016       0  235.66     .12       0
Bank Sta=107.9,137.3
XS Rating Curve= 0 ,0
Exp/Cntr=0.3,0.1

Type RM Length L Ch R = 1 ,2530.5  ,249.8,258.9,268.2
XS GIS Cut Line= 3
      1831258.46      170688.307     1831069.378      170824.143
     1830983.475      170818.093
#Sta/Elev= 21
       0 1824.89     9.7 1823.05    38.8  1818.2   106.7 1807.06   116.4 1805.31
   126.1 1803.44   135.8 1802.05   145.5 1801.52   155.2 1802.74  157.281803.336
   164.9 1805.52   174.6 1808.91   184.3 1811.49     194 1813.27  199.211814.103
   203.7 1814.82   213.4 1816.11   232.8 1817.96     252 1820.54   261.5 1821.69
   318.9  1827.9
#Mann= 4 ,-1 , 0
       0     .12       0   126.1    .045       0  157.28    .016       0
  199.21     .12       0
Bank Sta=126.1,157.28
XS Rating Curve= 0 ,0
Exp/Cntr=0.3,0.1

Type RM Length L Ch R = 1 ,2271.6  ,189.5,196.5,203.6
XS GIS Cut Line= 2
     1831127.379      170511.964     1830890.281      170602.061
#Sta/Elev= 19
       0 1814.96     9.8 1812.96    19.5 1811.27      39 1808.33    48.8 1807.15
    68.3  1805.1   107.3 1801.41   117.1  1800.3   126.8 1799.11   136.6 1798.52
   146.3 1799.59   147.8  1800.1   156.1 1802.89  161.46  1805.1   165.8 1806.89
   175.6 1810.48  199.051818.198   214.6 1823.38   253.6 1836.79
#Mann= 5 ,-1 , 0
       0     .12       0   117.1    .045       0   147.8     .12       0
  161.46    .016       0  199.05     .12       0
Bank Sta=117.1,147.8
XS Rating Curve= 0 ,0
Exp/Cntr=0.3,0.1

Type RM Length L Ch R = 1 ,2075.1  ,162.6,169.2,175.7
XS GIS Cut Line= 2
      1831091.15      170347.476     1830862.493      170387.513
#Sta/Elev= 29
       0 1809.87     9.7 1808.76    19.3 1807.84      29 1806.92    38.7 1806.02
    48.4 1805.15      58 1804.28    67.7 1803.43    77.4 1802.57      87 1801.68
    96.7 1800.78   106.4  1799.8   116.1 1798.62   125.7 1797.46     129  1797.3
   135.4    1797     144 1798.13   145.1 1798.28   154.8 1801.24   164.4 1804.67
   174.1 1807.77   183.8 1810.67  187.471811.767   193.4 1813.54   203.1 1816.39
   212.8 1819.05   222.5  1821.4  224.121821.761   232.1 1823.54
#Mann= 5 ,-1 , 0
       0     .12       0   116.1    .045       0   145.1     .12       0
  187.47    .016       0  224.12     .12       0
Bank Sta=116.1,145.1
XS Rating Curve= 0 ,0
Exp/Cntr=0.3,0.1

Type RM Length L Ch R = 1 ,1905.9  ,179.2,178.6,177.9
XS GIS Cut Line= 2
     1831084.103      170202.594      1830880.11      170202.594
#Sta/Elev= 26
       0 1810.43     9.7 1809.07    19.4 1807.78    29.1 1806.49    38.9 1805.14
    48.6 1803.71    58.3 1802.19      68 1800.61    77.7 1799.03    87.4 1797.12
    97.1 1794.89   103.7 1793.73   106.8 1793.19   116.6 1793.61   118.7 1794.23
   126.3 1796.49     136 1800.01   145.7 1802.49   155.4 1804.13  163.331805.446
   165.1 1805.74   174.8 1807.54   184.6 1809.49   194.3 1811.54  200.56 1812.85
     204 1813.57
#Mann= 5 ,-1 , 0
       0     .12       0    97.1    .045       0   118.7     .12       0
  163.33    .016       0  200.56     .12       0
Bank Sta=97.1,118.7
XS Rating Curve= 0 ,0
Exp/Cntr=0.3,0.1

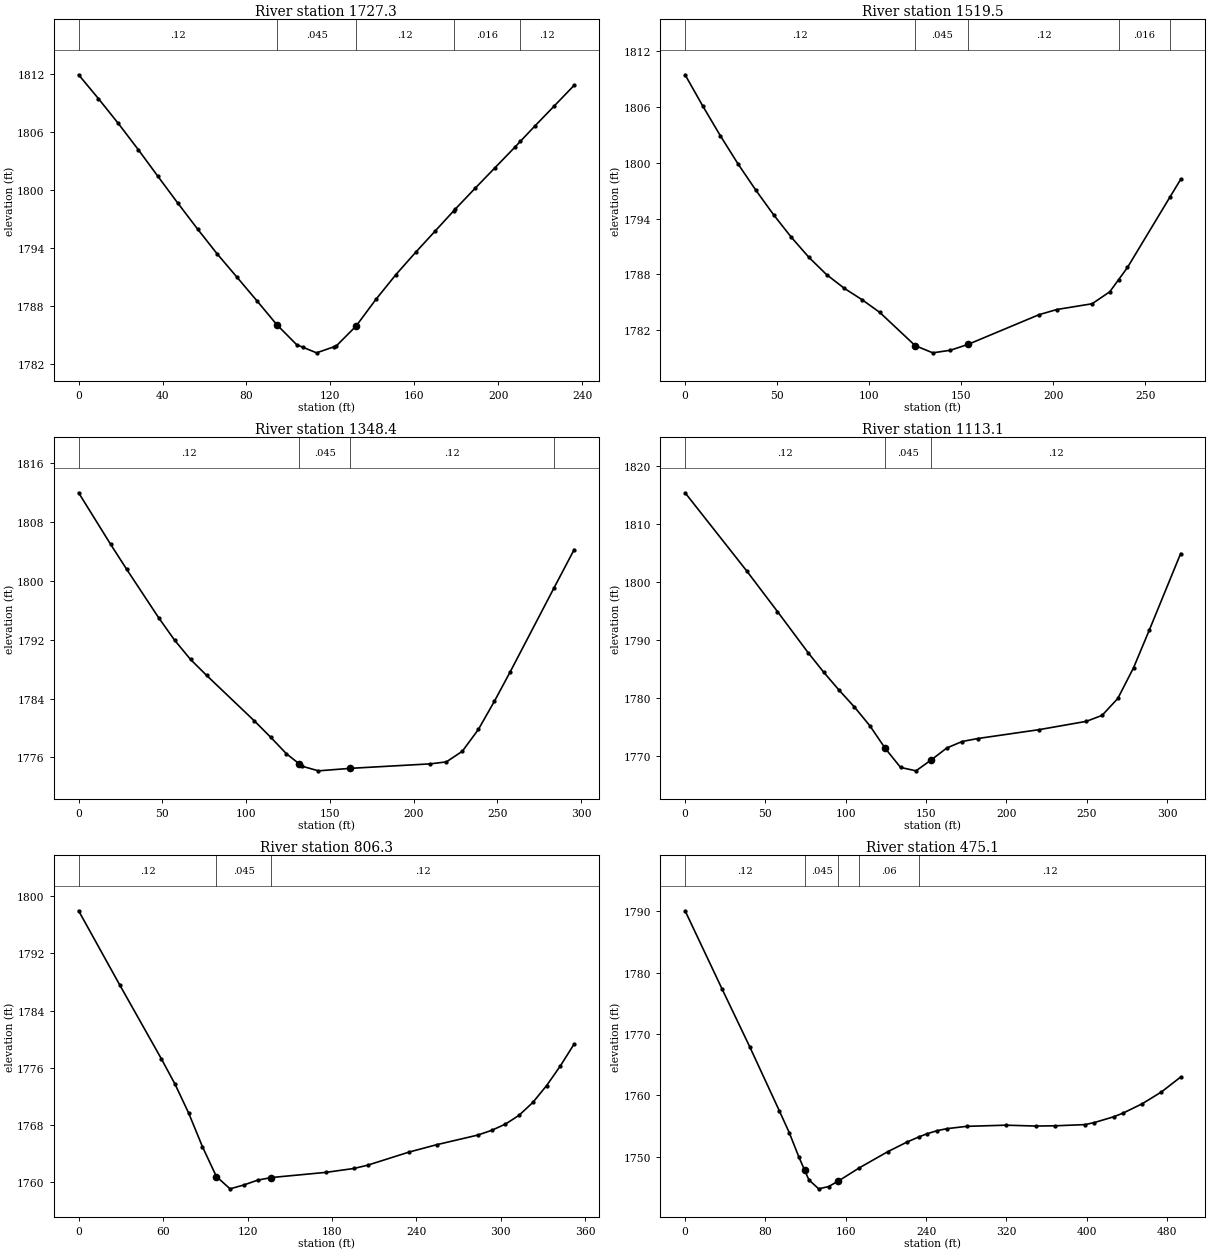
Type RM Length L Ch R = 1 ,1727.3  ,202.5,207.7,213.1
XS GIS Cut Line= 2
      1831102.13      170022.715     1830865.942      170026.933
#Sta/Elev= 30
       0 1811.97     9.4 1809.51    18.9 1806.93    28.4 1804.22    37.8 1801.44
    47.2 1798.69    56.7 1795.98    66.1 1793.39    75.6 1790.96      85 1788.54
    94.5 1786.06   103.9    1784   106.9 1783.73   113.4 1783.15   121.9 1783.79
   122.8 1783.86   132.3 1785.94   141.7 1788.69   151.2 1791.25   160.6 1793.56
   170.1 1795.81  178.831797.881   179.5 1798.04     189 1800.21   198.4 1802.32
   207.9 1804.46  210.611805.083   217.3 1806.62   226.8 1808.76   236.2 1810.88
#Mann= 5 ,-1 , 0
       0     .12       0    94.5    .045       0   132.3     .12       0
  178.83    .016       0  210.61     .12       0
Bank Sta=94.5,132.3
XS Rating Curve= 0 ,0
Exp/Cntr=0.3,0.1

Type RM Length L Ch R = 1 ,1519.5  ,170.5,171.1,171.5
XS GIS Cut Line= 2
     1831144.879      169835.849     1830877.644      169802.838
#Sta/Elev= 24
       0 1809.47     9.6 1806.11    19.2  1802.9    28.8 1799.87    38.5 1797.04
    48.1 1794.41    57.7    1792    67.3 1789.83    76.9 1787.97    86.6 1786.49
    96.2 1785.27   105.8 1783.91     125 1780.34   134.6 1779.56   144.2 1779.84
   153.9 1780.48   192.3 1783.66     202 1784.22   221.2 1784.84   230.8 1786.13
  235.641787.446   240.4 1788.74  263.551796.337   269.3 1798.21
#Mann= 5 ,-1 , 0
       0     .12       0     125    .045       0   153.9     .12       0
  235.64    .016       0  263.55     .12       0
Bank Sta=125,153.9
XS Rating Curve= 0 ,0
Exp/Cntr=0.3,0.1

Type RM Length L Ch R = 1 ,1348.4  ,230.3,235.4,239.3
XS GIS Cut Line= 2
     1831192.821      169672.593     1830899.609      169632.537
#Sta/Elev= 22
       0 1811.99    19.1 1804.98    28.6 1801.61    47.7 1795.02    57.3 1791.94
    66.8 1789.32    76.4 1787.15     105 1780.94   114.6 1778.75   124.1 1776.48
   131.8  1775.1   133.6 1774.78   143.2 1774.16   162.3  1774.5     210 1775.11
   219.6 1775.38   229.1 1776.82   238.7 1779.79   248.2  1783.6   257.8 1787.67
  283.851799.045   295.9 1804.26
#Mann= 4 ,-1 , 0
       0     .12       0   131.8    .045       0   162.3     .12       0
  283.85    .016       0
Bank Sta=131.8,162.3
XS Rating Curve= 0 ,0
Exp/Cntr=0.3,0.1

Type RM Length L Ch R = 1 ,1113.1  ,314.7,306.8,298.9
XS GIS Cut Line= 3
     1831235.753      169463.647     1831022.601      169407.758
     1830934.968      169416.659
#Sta/Elev= 22
       0 1815.37    38.3  1801.9    57.5 1794.87    76.6 1787.77    86.2 1784.43
    95.8 1781.32   105.4  1778.4     115 1775.16   124.6 1771.25   134.1 1767.98
   143.7 1767.39   153.3  1769.3   162.9 1771.34   172.4 1772.45     182 1772.96
   220.4  1774.5   249.7 1775.93   259.5 1776.96   269.3 1779.88   279.1 1785.18
   288.9 1791.68   308.4 1804.88
#Mann= 3 ,-1 , 0
       0     .12       0   124.6    .045       0   153.3     .12       0
Bank Sta=124.6,153.3
XS Rating Curve= 0 ,0
Exp/Cntr=0.3,0.1

Type RM Length L Ch R = 1 ,806.3   ,331.1,331.2,331.3
XS GIS Cut Line= 2
     1831294.669       169141.59     1830943.078      169123.524
#Sta/Elev= 24
       0 1797.96    29.3 1787.55    58.7 1777.28    68.5  1773.7    78.2 1769.65
      88 1764.94    97.9 1760.78   107.6 1759.06   117.4  1759.6   127.1 1760.27
   136.9 1760.64     176 1761.37   195.6 1761.91   205.4 1762.37   234.7  1764.2
   254.3 1765.23   283.6 1766.58   293.4 1767.24   303.2 1768.11   312.9 1769.34
   322.7 1771.14   332.5  1773.5   342.3 1776.26   352.1 1779.33
#Mann= 3 ,-1 , 0
       0     .12       0    97.9    .045       0   136.9     .12       0
Bank Sta=97.9,136.9
XS Rating Curve= 0 ,0
Exp/Cntr=0.3,0.1

Type RM Length L Ch R = 1 ,475.1   ,207,206.4,205.4
XS GIS Cut Line= 4
     1831361.737      168850.835     1831308.231      168815.015
     1830974.858      168798.383     1830892.481      168846.514
#Sta/Elev= 29
       0 1790.06    36.8 1777.34    64.4 1767.92    93.8 1757.53   103.7 1753.97
   113.5 1749.92   119.1 1747.83   123.3 1746.27   133.1 1744.81   142.9 1745.18
   152.7 1746.08  173.621748.234   201.8 1750.85   221.5 1752.46  232.741753.251
   241.1 1753.78   250.9 1754.27   260.7  1754.6   280.4 1754.98   319.6 1755.17
   349.1 1755.03   368.7 1755.07   398.2 1755.26   407.7  1755.6   426.8 1756.53
   436.3 1757.14   455.4 1758.66   474.5 1760.58   493.6    1763
#Mann= 5 ,-1 , 0
       0     .12       0   119.1    .045       0   152.7     .12       0
  173.62     .06       0  232.74     .12       0
Bank Sta=119.1,152.7
XS Rating Curve= 0 ,0
Exp/Cntr=0.3,0.1

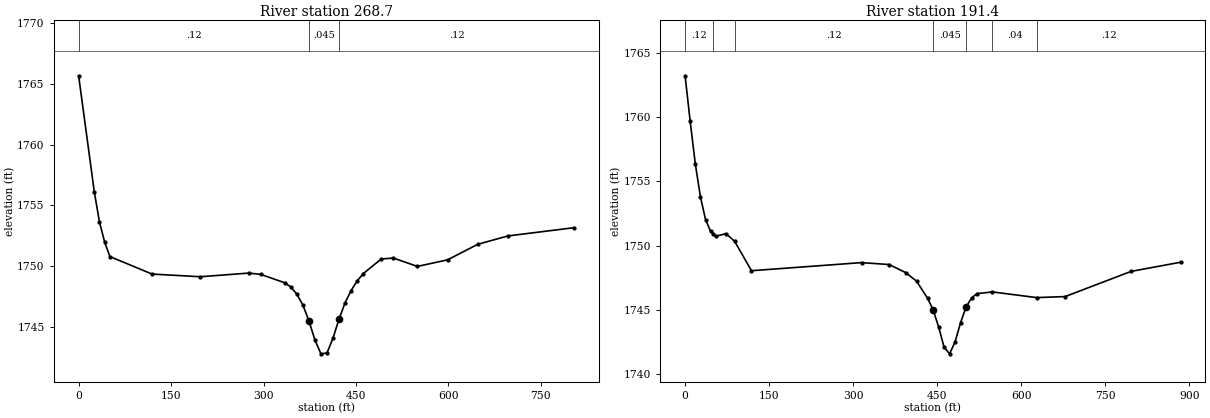
Type RM Length L Ch R = 1 ,268.7   ,77,77.3,77.3
XS GIS Cut Line= 3
     1831621.964      168659.369     1831594.552      168616.678
     1830841.484       168595.44
#Sta/Elev= 30
       0 1765.68    25.4 1756.13    33.8 1753.64    42.3 1751.97    50.7 1750.79
   119.2 1749.35   197.5 1749.13   275.8 1749.43   295.3 1749.33   334.5 1748.63
   344.2 1748.29     354  1747.7   363.8 1746.81   373.6 1745.51   383.4 1743.93
   393.2 1742.78     403 1742.85   412.7 1744.06   422.5 1745.64   432.3 1746.98
   442.1 1747.99   451.9 1748.78   461.7 1749.38     491 1750.59   510.6 1750.67
   549.7 1749.98   598.6 1750.52   647.6  1751.8   696.5 1752.49   804.1 1753.17
#Mann= 3 ,-1 , 0
       0     .12       0   373.6    .045       0   422.5     .12       0
Bank Sta=373.6,422.5
XS Rating Curve= 0 ,0
Exp/Cntr=0.3,0.1

Type RM Length L Ch R = 1 ,191.4   ,190.3,191.4,192.5
XS GIS Cut Line= 3
      1831662.87      168639.563     1831596.386      168541.439
      1830830.74      168517.931
#Sta/Elev= 30
       0  1763.2     9.1 1759.65    18.2 1756.36    27.4 1753.79    36.5 1752.02
    45.6  1751.1   49.741750.932    54.7 1750.73    72.9 1750.93   88.351750.343
   118.5 1748.05   314.9 1748.68     364 1748.53   393.5 1747.91   413.1 1747.24
   432.8 1745.91   442.6 1745.02   452.4  1743.7   462.2 1742.12   472.1 1741.59
   481.9 1742.52   491.7 1744.01   501.5 1745.23   511.4 1745.94   521.2 1746.27
  548.661746.402  627.441745.961   678.3 1746.04   796.2    1748   884.5 1748.71
#Mann= 7 ,-1 , 0
       0     .12       0   49.74    .016       0   88.35     .12       0
   442.6    .045       0   501.5     .12       0  548.66     .04       0
  627.44     .12       0
Bank Sta=442.6,501.5
XS Rating Curve= 0 ,0
Exp/Cntr=0.3,0.1

Chan Stop Cuts=-1
Use User Specified Reach Order=0
Composite Channel Slope=5